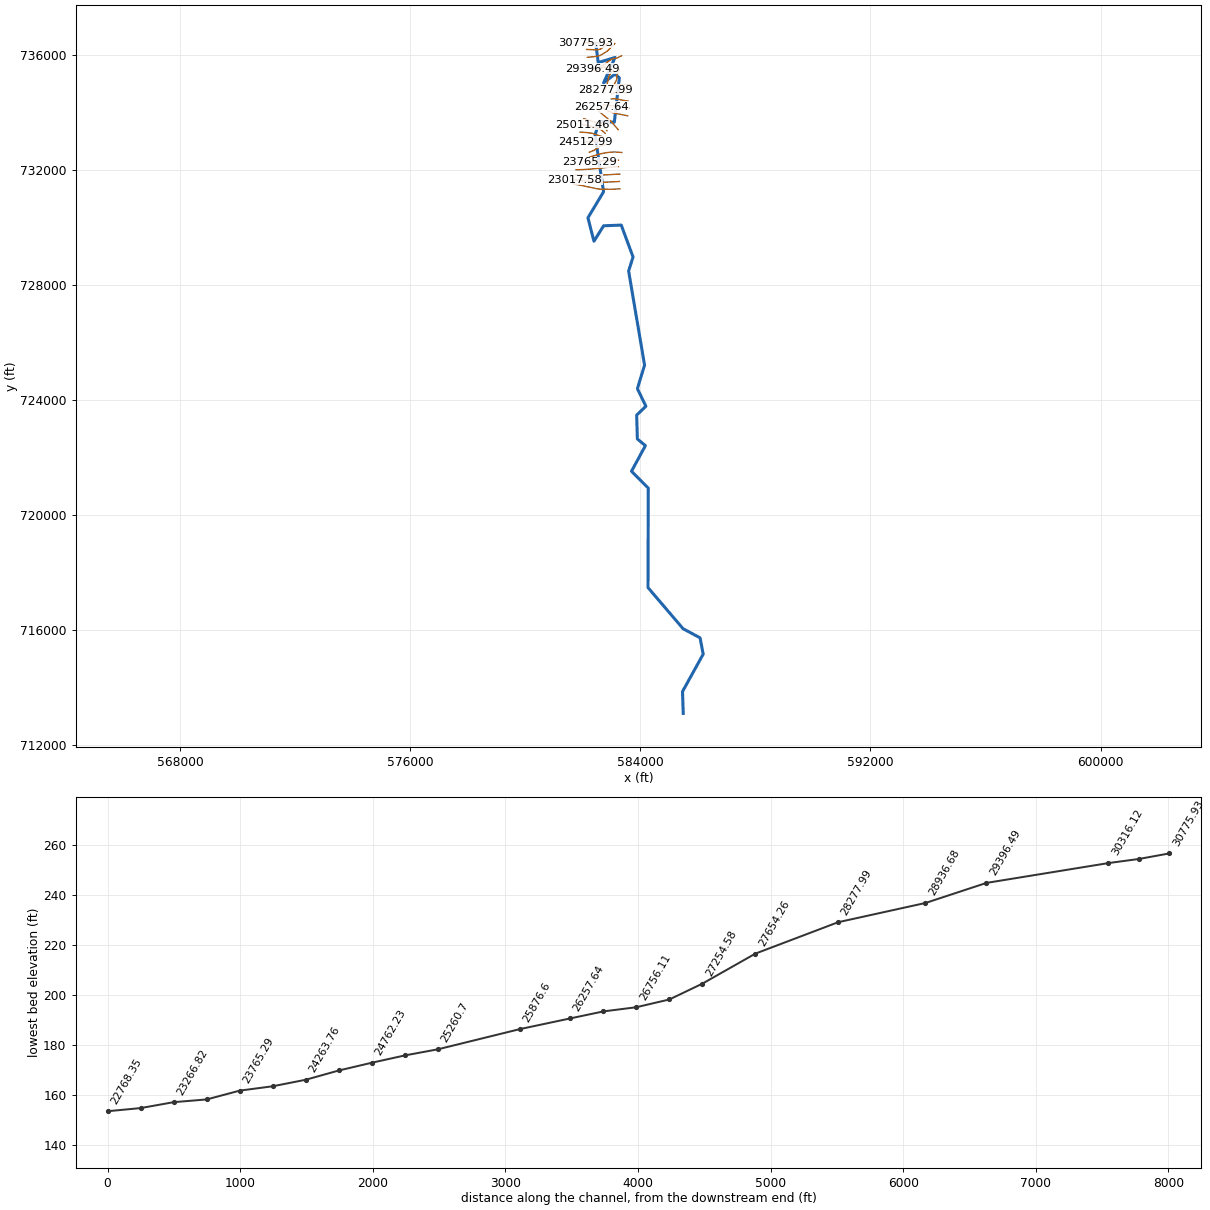
--- 2351_ras.prj (project) ---

Proj Title=2351
Current Plan=p01
Default Exp/Contr=0.3,0.1
English Units
Geom File=g01
Flow File=f01
Plan File=p01
Y Axis Title=Elevation
X Axis Title(PF)=Main Channel Distance
X Axis Title(XS)=Station
BEGIN DESCRIPTION:
RFD model 2351 exported to HEC-RAS
END DESCRIPTION:

--- 2351_ras.p01 (plan) ---

Plan Title=Plan 01
Program Version=4.10
Short Identifier=Plan 01
Geom File=g01
Flow File=f01
Subcritical Flow
Calc Critical at every XS
Secant Critical Depth

--- 2351_ras.f01 (steady flow) ---

Flow Title=Flow 01
Program Version=5.01
Number of Profiles= 6
Profile Names=10yr,25yr,50yr,100yr,100plus,500yr
River Rch & RM=2351,66,30775.93
 3343.74 5587.79 7780.97 9854.9714388.26 17006.4
River Rch & RM=2351,66,30546.03
 3346.66 5593.47 7789.63 9866.7914405.5117027.15
River Rch & RM=2351,66,30316.12
 3349.35 5598.71 7797.61 9877.6614421.3917046.24
River Rch & RM=2351,66,29396.49
  3365.7  5630.7 7846.43  9944.414518.8217163.88
River Rch & RM=2351,66,28936.68
 3367.94 5635.12 7853.21 9953.7114532.4217180.43
River Rch & RM=2351,66,28277.99
 3371.03 5641.34 7862.84 9967.0214551.85 17204.4
River Rch & RM=2351,66,27654.26
 3373.37 5646.06 7870.14 9977.1114566.5817222.59
River Rch & RM=2351,66,27254.58
 3459.73 5811.37 8119.7310315.4415060.5417807.02
River Rch & RM=2351,66,27005.34
 3461.44  5814.8 8125.0210322.74 15071.217820.06
River Rch & RM=2351,66,26756.11
 3463.16 5818.23 8130.3110330.0415081.8617833.11
River Rch & RM=2351,66,26506.87
 3487.86 5867.91 8207.2910436.5215237.3118024.24
River Rch & RM=2351,66,26257.64
 3489.46 5871.19 8212.4110443.6615247.7418037.22
River Rch & RM=2351,66, 25876.6
 3496.06 5884.71 8233.55 10473.115290.7218090.74
River Rch & RM=2351,66, 25260.7
 3541.81 5975.93 8374.2610667.1815574.0818436.32
River Rch & RM=2351,66,25011.46
  3549.2 5990.94 8397.6610699.6915621.5518495.01
River Rch & RM=2351,66,24762.23
  3550.1 5992.78 8400.5210703.6815627.3718502.24
River Rch & RM=2351,66,24512.99
  3553.8 6000.32 8412.3110720.0815651.3218531.96
River Rch & RM=2351,66,24263.76
 3589.36 6072.76 8525.3110877.3215880.8818816.11
River Rch & RM=2351,66,24014.52
 3614.16  6123.6 8604.8910988.36   1604319017.59
River Rch & RM=2351,66,23765.29
 3615.35 6126.11 8608.8610993.9516051.1719027.92
River Rch & RM=2351,66,23516.05
 3617.36 6130.35 8615.5811003.4216064.9919045.39
River Rch & RM=2351,66,23266.82
 3620.48 6136.91 8625.9811018.0516086.3519072.39
River Rch & RM=2351,66,23017.58
 3646.25 6190.88 8711.3411138.1216261.6619293.36
River Rch & RM=2351,66,22768.35
 3649.26  6197.2 8721.3811152.2616282.2919319.43
River Rch & RM=2351,66,22519.11
 3650.31 6199.45 8724.9611157.3416289.7219328.91
River Rch & RM=2351,66,22159.83
 3675.07 6251.11 8806.5611272.0216457.14 19539.3
River Rch & RM=2351,66,22069.32
 3675.33 6251.66 8807.4511273.2716458.9819541.65
River Rch & RM=2351,66,21443.68
 3702.69 6309.71 8899.8811403.9816649.8219784.02
River Rch & RM=2351,66, 19222.6
    3742 6394.99 9037.1611599.7116935.5820152.01
River Rch & RM=2351,66,18637.75
  3746.3 6404.33  9052.211621.1716966.9120192.39
River Rch & RM=2351,66,17927.28
 3976.93 6884.32 9811.1412689.86 18527.222142.43
River Rch & RM=2351,66,17518.88
    3983  6897.4 9832.2112719.9418571.1222198.55
River Rch & RM=2351,66,17244.67
 3986.87 6905.75 9845.6612739.1718599.1822234.44
River Rch & RM=2351,66,17123.94
 3990.45 6913.67 9858.5412757.7118626.2622269.56
River Rch & RM=2351,66,16809.34
 4002.58 6940.22 9901.5912819.5218716.5122385.96
River Rch & RM=2351,66, 16565.9
 4010.78 6958.27 9930.9312861.7318778.1222465.66
River Rch & RM=2351,66,16322.46
 4021.62 6982.15 9969.7512917.6118859.7122571.26
River Rch & RM=2351,66,16079.02
 4023.83 6987.02 9977.67   1292918876.35 22592.8
River Rch & RM=2351,66,15835.58
 4027.95 6996.16 9992.5912950.5218907.7622633.64
River Rch & RM=2351,66,15592.14
 4036.67 7016.15 10025.712998.8118978.2622727.08
River Rch & RM=2351,66, 15348.7
 4047.94 7041.0910066.3513057.4319063.8422838.12
River Rch & RM=2351,66,15105.26
 4049.86  7045.510073.6713068.1119079.4422858.83
River Rch & RM=2351,66,14861.82
 4055.72  7058.8 10095.6   13100   1912622920.15
River Rch & RM=2351,66,14618.38
 4065.58 7081.2510132.6813153.9919204.83 23024.2
River Rch & RM=2351,66,14374.94
 4066.95  7084.4 10137.913161.6119215.9523038.94
River Rch & RM=2351,66,14131.51
 4067.63 7086.0410140.67 13165.719221.9323047.04
River Rch & RM=2351,66,13888.07
 4071.21 7094.8710155.7313188.1319254.6723091.98
River Rch & RM=2351,66,13644.63
 4091.52  7142.510235.4213305.2519425.6623321.28
River Rch & RM=2351,66,13401.19
 4092.16 7144.0910238.1313309.2719431.5423329.35
River Rch & RM=2351,66,13157.75
 4094.47 7149.7310247.7313323.5719452.4123357.95
River Rch & RM=2351,66,12914.31
 4095.28 7151.7410251.1713328.6919459.8823368.21
River Rch & RM=2351,66,12670.87
 4095.69 7152.7510252.8913331.2519463.6323373.34
River Rch & RM=2351,66,11946.49
 4117.97 7208.0210347.5313472.6119670.0123657.75
River Rch & RM=2351,66,10980.64
    4150 7287.6510484.0613676.8119968.1524069.19
River Rch & RM=2351,66,10497.72
 4152.47 7294.2810495.7413694.6119994.1324106.13
River Rch & RM=2351,66,10256.26
 4153.36 7296.6910500.0413701.1820003.7224119.88
River Rch & RM=2351,66,9531.879
 4156.81 7305.9110516.2913725.9320039.8524171.25
River Rch & RM=2351,66,8951.781
 4168.24 7336.2710569.6713807.1620158.4524339.55
River Rch & RM=2351,66,8823.774
 4168.37 7336.6410570.3413808.1920159.9524341.71
River Rch & RM=2351,66,8265.542
 4301.51  7645.611086.5814567.6121268.7125822.34
River Rch & RM=2351,66,7794.766
 4307.42 7661.6911115.2314611.6321332.9725914.59
River Rch & RM=2351,66,7585.843
 4307.82 7662.7911117.1914614.6421337.3825920.93
River Rch & RM=2351,66, 6963.15
 4310.05 7669.0811128.5314632.2121363.0225958.21
River Rch & RM=2351,66,5340.526
 4316.04 7686.5811160.4314681.9721435.6726065.03
Boundary for River Rch & Prof#=2351,66,1
Up Type= 0
Dn Type= 2
Boundary for River Rch & Prof#=2351,66,2
Up Type= 0
Dn Type= 2
Boundary for River Rch & Prof#=2351,66,2
Up Type= 0
Dn Type= 2
Boundary for River Rch & Prof#=2351,66,2
Up Type= 0
Dn Type= 2
Boundary for River Rch & Prof#=2351,66,2
Up Type= 0
Dn Type= 2
Boundary for River Rch & Prof#=2351,66,2
Up Type= 0
Dn Type= 2

--- 2351_ras.g01 (geometry) ---

Geom Title=2351
Program Version=4.10

River Reach=2351,66
Reach XY= 30
582446.998735009736396.768682872582533.463281275735722.200505088
583119.924194335 735901.29866561582719.746351094735017.286621131
583119.808363734735324.876951036583266.559726148735189.862544691
 583093.60495749733650.202360575582568.597413095733678.901670764
582423.930686415733209.007306036582718.619729398731228.389671116
582175.545452504   730326.532347582383.887708128729510.300529344
582719.743337781730047.260671345 583333.92705217730072.327394838
 583744.53218287728962.436848338583589.547624886728476.962539939
584144.609434785725202.322768357583895.252607406724385.029001444
584191.125501512723772.084395625583869.820404947723465.370998485
583894.011861505722634.670236621584174.033278495722402.094858334
583690.310556503721512.274784234584273.234502196720925.837037766
584264.390039234 717466.48073789585485.692710372716035.024250113
586074.670488507715720.730659606586182.712033181715151.002276518
585463.962033183713853.259220933585489.416389199713093.317635081

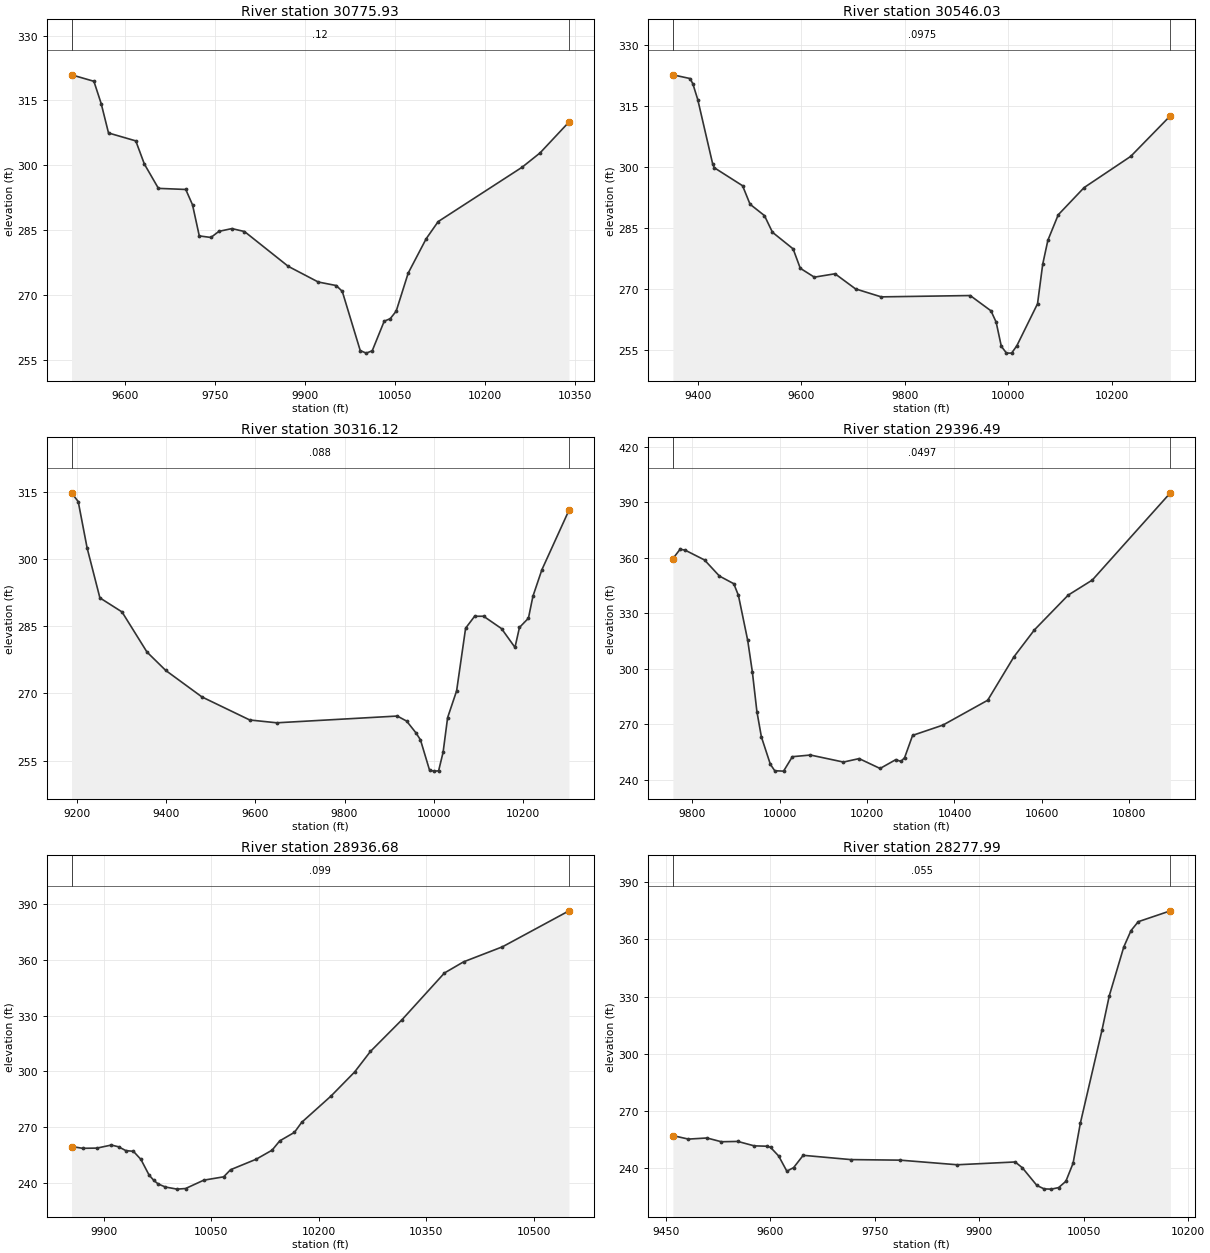
Type RM Length L Ch R = 1 ,30775.93,229.907200,229.907200,229.907200
XS GIS Cut Line= 6
582895.613435397736565.656418041582819.358592972736512.437026484
 582712.24065974736451.426122167582574.521493435736405.867489786
582463.595206292736395.557360289582106.739317392736406.857660575
#Sta/Elev= 30
9510.079320.92749547.411319.43229559.606  314.25  9571.8307.46969617.311305.6379
9631.631300.28419655.083294.65179700.742294.39569712.022290.84059723.302283.6482
9742.715283.28929756.057 284.7019777.684285.3413 9798.73284.66559871.829276.6057
9921.842272.98169951.955  272.16 9961.96270.81849991.972257.108410001.97256.5214
10011.98257.066610031.99263.918210041.99  264.49   10052 266.24310072.01275.0434
10102.03282.997310122.04286.962110262.11299.541610292.13302.860610340.41310.0063
#Mann= 3 , 0 , 0
9510.079    0.12       09510.079    0.12       010340.41    0.12       0
#XS Ineff= 2 , 0
       0                               0
Bank Sta=9510.079,10340.41
Exp/Cntr=0.3,0.1

Type RM Length L Ch R = 1 ,30546.03,229.907100,229.907100,229.907100
XS GIS Cut Line= 6
582973.482092533736497.371595624582719.524053935736260.353469563
582608.711468301 736192.12806412582547.222191348736174.088685285
582450.622888394 736165.88563873582128.428744755736179.520329313
#Sta/Elev= 30
9351.738322.58379384.914321.67119390.309320.36159399.714316.5217 9428.61300.7146
9431.683299.7897  9486.4295.37179500.848290.8336 9528.67 288.0479544.191283.9503
9584.091279.88299597.946275.12059625.068  272.949665.141273.7698 9704.81270.0575
9754.457268.10319926.479  268.439966.596264.6822  9976.6261.91669986.603255.9836
9996.605254.299910006.61254.311910016.61256.103410056.63266.409610066.64276.1058
10076.65281.994910096.67 288.24310146.73294.922910236.82302.577610313.48312.5429
#Mann= 3 , 0 , 0
9351.738  0.0975       09351.738  0.0975       010313.48  0.0975       0
#XS Ineff= 2 , 0
       09867.554                       0
Bank Sta=9351.738,10313.48
Exp/Cntr=0.3,0.1

Type RM Length L Ch R = 1 ,30316.12,919.628500,919.628500,919.628500
XS GIS Cut Line= 6
 583109.45581755736385.705679968582854.005447865736125.094696775
582607.586151958735971.566444322582456.527262062 735936.84902674
582361.932015806735925.096160278582154.567848593735905.543796748
#Sta/Elev= 30
9188.587314.72599203.578312.76169223.524 302.4039252.096291.29559301.598288.1636
9357.609279.20479399.618275.10639480.667269.20139587.691264.06219648.249263.4347
9918.035264.94119938.998263.81859959.757261.21049969.993259.6282 9990.41 252.847
10000.54252.655810010.62252.7167 10020.7256.877610030.77264.581110050.93270.5569
10071.08284.535610091.23287.190210111.33287.204710151.51284.445110181.64280.2501
10191.68284.704910211.77286.761110221.82291.651210241.91297.576610302.61310.8513
#Mann= 3 , 0 , 0
9188.587   0.088       09188.587   0.088       010302.61   0.088       0
#XS Ineff= 2 , 0
       09859.446                       0
Bank Sta=9188.587,10302.61
Exp/Cntr=0.3,0.1

Type RM Length L Ch R = 1 ,29396.49,459.814300,459.814300,459.814300
XS GIS Cut Line= 6
583349.409274995 735957.62189357583181.029650182735879.792976677
583008.823853821735847.711719632582702.183004886 735632.63937214
582558.603508413735544.639035583582329.339473724735502.954665631
#Sta/Elev= 30
9756.062359.66619772.483364.70169783.879364.22979828.299358.90719862.405350.2051
 9895.28346.0587 9905.89339.72349927.111   315.49937.721298.38829948.118276.9569
9958.375263.26739978.888248.43949988.974244.931910009.11244.727810029.22252.5285
 10070.6253.432610146.03249.629310181.96251.496410229.85246.163210265.78250.9408
10277.75249.955910286.05252.069510304.23264.053310373.55269.610610475.98283.0551
10536.01306.551710582.92321.123410660.11339.900110715.28  348.0510893.82395.2091
#Mann= 3 , 0 , 0
9756.062  0.0497       09756.062  0.0497       010893.82  0.0497       0
#XS Ineff= 2 , 0
       0                               0
Bank Sta=9756.062,10893.82
Exp/Cntr=0.3,0.1

Type RM Length L Ch R = 1 ,28936.68,658.685800,658.685800,658.685800
XS GIS Cut Line= 6
583030.358575642735454.365503117582958.421989471735448.286354989
582928.900584519735457.772949561582801.832796067735551.606058642
582734.142763406735567.492304906582396.423760802735438.999587476
#Sta/Elev= 30
9855.273259.64019870.687258.67139890.758258.78259910.829260.42589920.865259.4789
9931.061 257.4269941.564257.06399952.068252.6862 9963.44244.29019970.153241.3585
 9976.17239.47389986.313237.831210002.46236.705110014.34237.029310039.74241.5273
10067.51 243.32310077.11247.143210112.81252.790110135.03257.660510145.74262.6688
10166.25267.2518 10176.3272.617510217.36 286.81810250.15299.705310272.25310.7863
10316.46327.919610375.51352.995810402.22358.996610456.48367.090510549.27 386.439
#Mann= 3 , 0 , 0
9855.273   0.099       09855.273   0.099       010549.27   0.099       0
#XS Ineff= 2 , 0
       0                               0
Bank Sta=9855.273,10549.27
Exp/Cntr=0.3,0.1

Type RM Length L Ch R = 1 ,28277.99,623.727500,623.727500,623.727500
XS GIS Cut Line= 6
583042.514477559735429.935184187583029.079321325735419.848737478
582988.992861271735384.583060816582898.643699586735237.542553335
582881.807041287 735121.01916641582785.166267931734780.593252659
#Sta/Elev= 30
9459.935257.08769482.168255.26099508.806255.84189529.494253.8722 9553.11254.0373
9576.584251.71989595.057251.52479600.058250.94219611.795246.40049623.532238.4268
 9633.26240.30629647.005246.75239715.379244.50719786.106244.21759868.277241.7943
9951.438243.26329961.833240.18059982.623 230.9349993.018  229.1310003.41229.0116
10013.81229.8118 10024.2233.1021 10034.6242.611310044.99263.545710076.18312.5584
10086.57330.445110107.37356.041110117.76364.644210128.16 369.32110174.32375.0224
#Mann= 3 , 0 , 0
9459.935   0.055       09459.935   0.055       010174.32   0.055       0
#XS Ineff= 2 , 0
       09909.836                       0
Bank Sta=9459.935,10174.32
Exp/Cntr=0.3,0.1

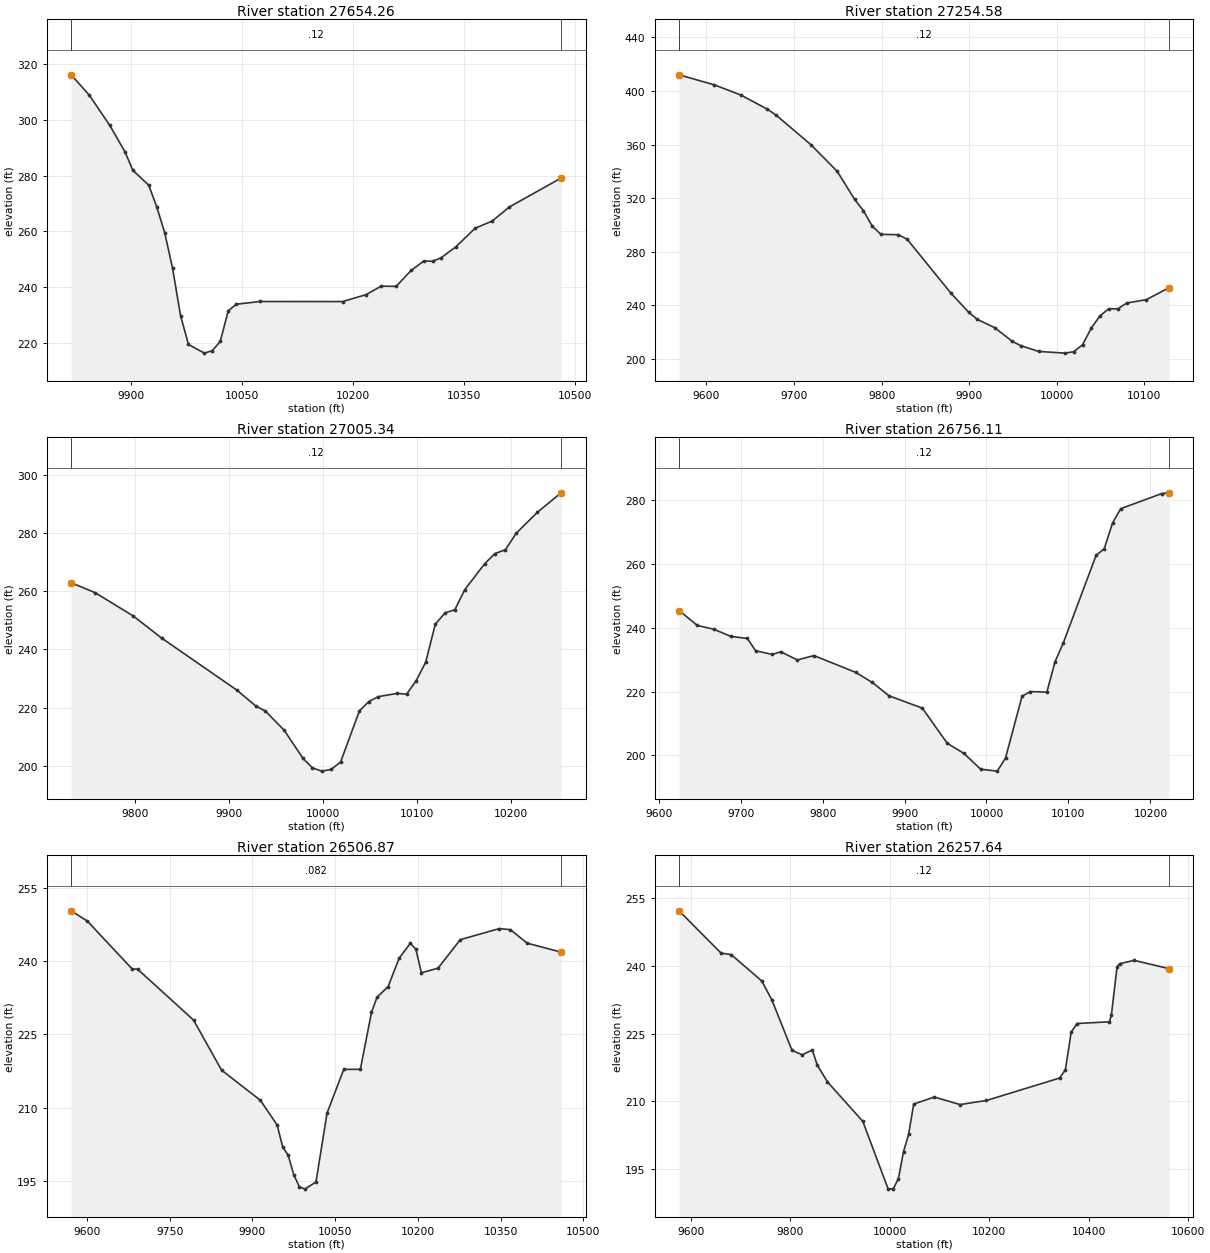
Type RM Length L Ch R = 1 ,27654.26,399.685100,399.685100,399.685100
XS GIS Cut Line= 6
583263.958312362735482.692816272583170.965661019735244.754050285
583179.797458827735173.725468963583171.240373015735139.223813996
583156.503684908735087.828034535583034.432201594734874.204445973
#Sta/Elev= 30
9819.275 316.0169843.884308.70779871.356297.96689891.954288.4972 9902.69 281.857
9924.163276.5076  9934.9268.82059945.637259.60839956.373246.7649 9967.11229.8872
9977.846219.5578 9999.32216.466210010.06217.348610020.79220.657110031.53231.5544
10042.27233.948110074.48234.935710186.26234.909110217.47237.359410238.36240.4202
10258.52240.343710278.67246.032610296.17249.459510307.69 249.31810319.21250.5689
10339.14 254.47210365.28 261.14710388.31 263.70410411.35268.715310481.37 279.088
#Mann= 3 , 0 , 0
9819.275    0.12       09819.275    0.12       010481.37    0.12       0
#XS Ineff= 2 , 0
       0                               0
Bank Sta=9819.275,10481.37
Exp/Cntr=0.3,0.1

Type RM Length L Ch R = 1 ,27254.58,249.234900,249.234900,249.234900
XS GIS Cut Line= 6
583665.384829521734955.271114916583235.380524755 734944.48526679
583192.936234266734946.712359071583168.288860857734944.787969962
583139.542219818734935.676559806583116.017842352734914.879910305
#Sta/Elev= 30
 9568.86411.95249609.258404.44879639.267396.91679669.277386.4862 9679.28382.0937
9719.293359.89539749.302340.07639769.308319.02039779.311310.69079789.315299.1298
9799.318292.99639819.324292.76799829.327289.28729879.343249.04529899.349235.0202
9909.352229.61679929.359223.38299949.365213.14599959.368209.93139979.374205.7252
10009.42204.460710019.43205.510310029.44 210.69510039.45223.209310049.47 232.387
 10059.5237.5775 10069.6237.415610079.93241.835510102.18 244.31610128.07253.1867
#Mann= 3 , 0 , 0
 9568.86    0.12       0 9568.86    0.12       010128.07    0.12       0
#XS Ineff= 2 , 0
       0                               0
Bank Sta=9568.86,10128.07
Exp/Cntr=0.3,0.1

Type RM Length L Ch R = 1 ,27005.34,249.234800,249.234800,249.234800
XS GIS Cut Line= 6
583500.364702682734667.417870822583315.913626759734691.119977915
583188.257833788734694.190492636583117.983576077734684.327314165
583081.305129136734673.461785959582992.979896968734629.428733931
#Sta/Elev= 30
9731.783262.93289757.385259.50559797.759251.53059828.039243.94199908.613225.9269
9928.697220.46459938.717218.80099958.759212.17279978.801202.48649988.811199.2421
9998.811 198.12710008.81198.706210018.82201.274110038.83218.824110048.85222.0487
10058.89223.748510078.98224.857710089.14224.6144 10099.3229.220910109.47235.5873
10119.71248.674110130.14252.580510140.57253.6594   10151260.502810172.48269.5353
 10183.3272.979910194.45274.3009 10205.8279.9227 10228.5287.170610253.68293.8646
#Mann= 3 , 0 , 0
9731.783    0.12       09731.783    0.12       010253.68    0.12       0
#XS Ineff= 2 , 0
       0                               0
Bank Sta=9731.783,10253.68
Exp/Cntr=0.3,0.1

Type RM Length L Ch R = 1 ,26756.11,249.234900,249.234900,249.234900
XS GIS Cut Line= 6
583577.032310665734380.773567497583208.947637933734447.777028226
583135.864638452734457.891628843583080.591485454734461.362408573
583021.591427554734460.233247054582986.313040925734456.459098164
#Sta/Elev= 30
9624.862245.44519647.196240.74949667.498239.55979687.832237.33119708.167236.6754
9718.334232.82629738.668231.64479748.835232.51069769.169229.93439789.504231.2979
9840.339226.02999860.674222.86119881.008 218.6729921.677214.80789952.178 203.755
9972.512200.57539992.846195.630710013.12195.025910023.21199.132910043.39218.5329
10053.48220.012110073.65219.807210083.67229.373610093.69235.271110133.76 262.762
10143.76264.875710153.76272.887410163.76277.405410213.92282.166810222.66282.3891
#Mann= 3 , 0 , 0
9624.862    0.12       09624.862    0.12       010222.66    0.12       0
#XS Ineff= 2 , 0
       0                               0
Bank Sta=9624.862,10222.66
Exp/Cntr=0.3,0.1

Type RM Length L Ch R = 1 ,26506.87,249.234900,249.234900,249.234900
XS GIS Cut Line= 6
 583593.85082917734135.913319727583493.575347473734154.034749502
583327.386259853734181.420716648583219.785070376734195.944304254
582922.883437773734229.856416397582714.115731927734260.101961666
#Sta/Elev= 30
 9571.11250.24349600.429248.15589681.701238.36499691.836238.29789793.185227.9011
9843.848217.68679914.483211.49759944.755206.45699954.834201.9814  9964.9200.2469
9974.966196.28059985.032193.84199995.098193.342210015.23194.810410035.36208.8988
10065.55217.818910095.75217.839710115.88229.461710125.94 232.56310146.07234.7593
 10166.2240.571210186.33243.589610196.39242.419110206.46237.573310236.65238.5241
10277.02244.348510347.75 246.60910367.96246.392610398.28243.6354 10459.8241.8015
#Mann= 3 , 0 , 0
 9571.11   0.082       0 9571.11   0.082       0 10459.8   0.082       0
#XS Ineff= 2 , 0
       0                               0
Bank Sta=9571.11,10459.8
Exp/Cntr=0.3,0.1

Type RM Length L Ch R = 1 ,26257.64,381.039900,381.039900,381.039900
XS GIS Cut Line= 6
583557.104602284733871.593521893583141.158352781733954.351332836
582992.145613032733992.544738755582925.840611738734018.996252309
582701.506093665734145.594155176582631.497601801 734178.45580954
#Sta/Elev= 30
9576.825252.18579661.065242.8385 9681.58242.48619742.745236.68399763.133232.4908
9803.846221.27379824.166220.30089844.485 221.3679854.645217.98289874.965214.3094
9946.084205.55399997.085190.551910007.32190.659610017.58192.835110027.84198.8505
 10038.1202.678710048.36209.3945 10089.8 210.94610141.52209.278410194.55210.1855
10341.51215.153810353.15216.9803 10364.8225.297910376.44227.228310441.74227.6093
10445.56229.054810457.02239.788510462.23240.466510491.19241.2178 10561.3239.3808
#Mann= 3 , 0 , 0
9576.825    0.12       09576.825    0.12       0 10561.3    0.12       0
#XS Ineff= 2 , 0
       0                10081.11       0
Bank Sta=9576.825,10561.3
Exp/Cntr=0.3,0.1

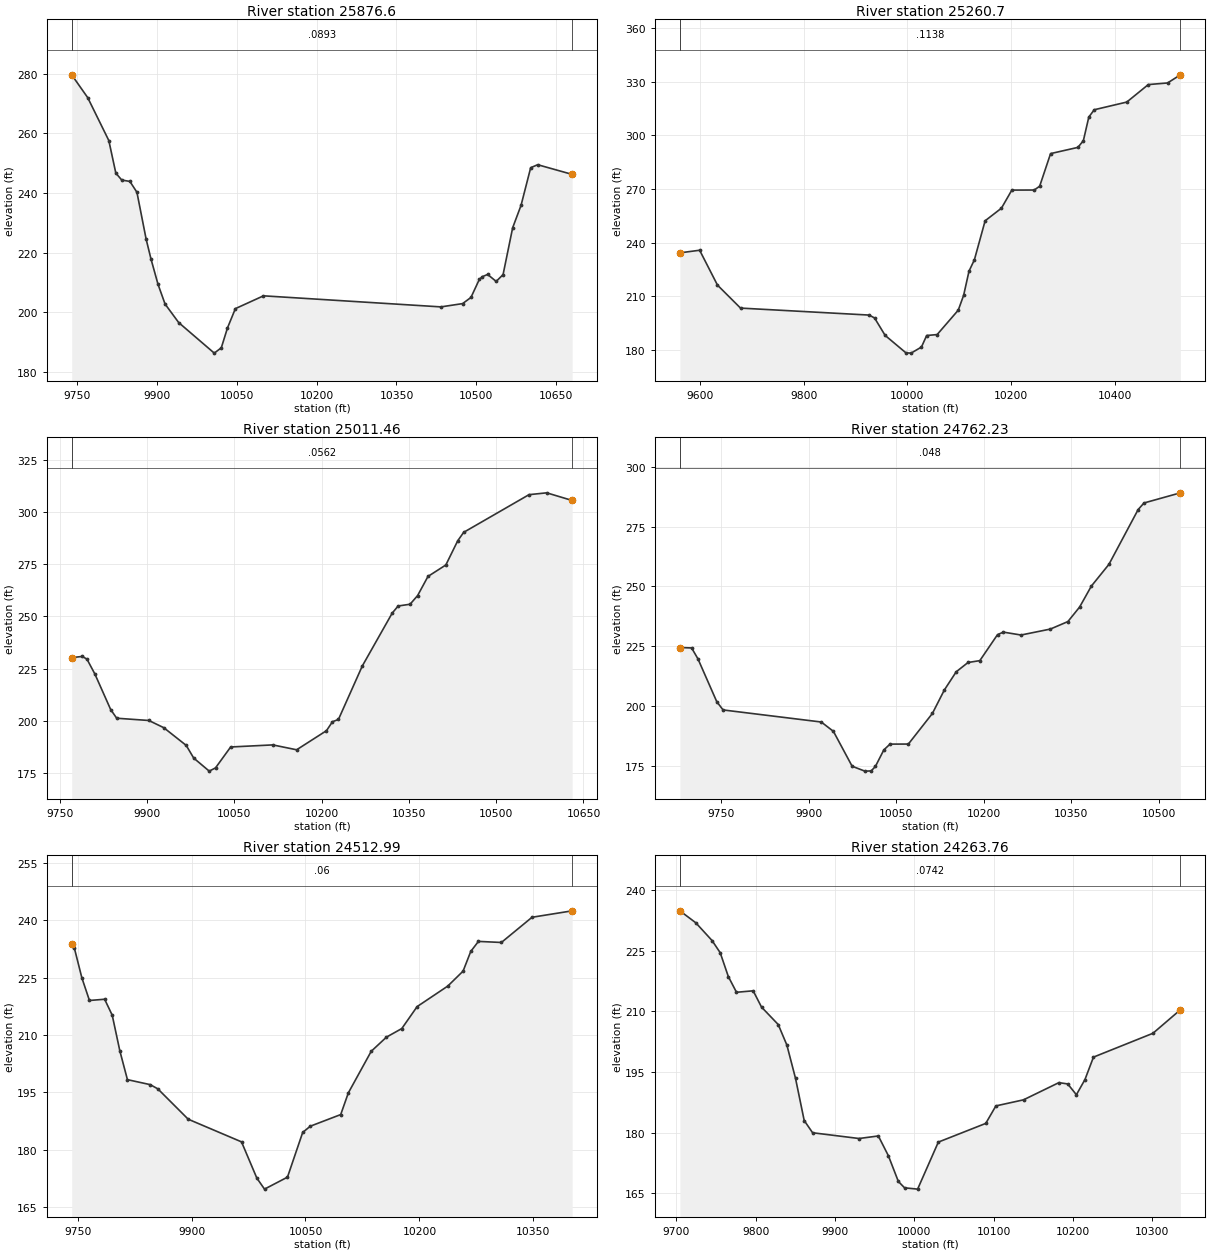
Type RM Length L Ch R = 1 , 25876.6,615.899700,615.899700,615.899700
XS GIS Cut Line= 3
583226.558396637733392.213723391582983.848619869733672.939881853
582544.927189976734036.355213657
#Sta/Elev= 30
9739.388279.6623 9769.51272.00829809.168257.61559822.387246.6667 9833.51244.3484
9848.826243.88539862.045240.2419 9879.38224.48799888.484217.84089901.703  209.34
9914.922202.74339940.539196.516810007.46186.256810020.68188.049310032.28194.7106
10047.12201.188510099.99205.488710433.56 201.77510474.36202.877710490.04204.9526
10505.72210.979210511.46211.920310521.41212.668410537.43 210.32410550.41212.6128
10568.45  228.3410584.13235.811610602.34248.490810615.49249.491610680.33246.2455
#Mann= 3 , 0 , 0
9739.388  0.0893       09739.388  0.0893       010680.33  0.0893       0
#XS Ineff= 2 , 0
       0                10152.01       0
Bank Sta=9739.388,10680.33
Exp/Cntr=0.3,0.1

Type RM Length L Ch R = 1 , 25260.7,249.234800,249.234800,249.234800
XS GIS Cut Line= 6
582839.562770301733351.808006217582735.669262463 733537.53000226
582654.376173275733609.839142467 582579.86679649733633.951520879
  582456.0192772733642.439787019582035.130668459733770.562980454
#Sta/Elev= 30
9560.908234.26959598.997235.71969633.435216.22279677.888203.38779926.188199.4837
9936.615197.85899956.998188.12389997.076  178.3910007.08178.214810027.08181.6102
10037.15188.059310057.38188.587310098.13202.2296 10108.5210.519610118.87224.0255
10129.25230.361910149.99252.181210181.44259.219710201.53 269.33210244.69 269.367
10255.23271.499910276.32289.734310329.02293.204710339.57296.937210350.11310.1689
10360.65314.246910423.36318.532610464.93328.315610502.07329.209310526.85333.7616
#Mann= 3 , 0 , 0
9560.908  0.1138       09560.908  0.1138       010526.85  0.1138       0
#XS Ineff= 2 , 0
       0                               0
Bank Sta=9560.908,10526.85
Exp/Cntr=0.3,0.1

Type RM Length L Ch R = 1 ,25011.46,249.234900,249.234900,249.234900
XS GIS Cut Line= 6
582774.350463985733262.628398308 582708.12840701733323.515686114
582605.393019705733406.555771508582536.432410298733447.162259682
582225.241284582733521.237261342581991.872766805733566.890360182
#Sta/Elev= 30
9770.348 230.2319788.627230.82539796.635229.49769810.219222.37569837.388205.3106
9847.726201.15759902.904200.07459928.621196.61479967.195188.11469980.054182.0401
10006.76175.762910017.57177.323810043.59187.353210115.95 188.35310156.99186.0062
10208.29195.182210218.55199.472810228.82200.560410269.86226.242810321.16251.5681
10331.42255.031610351.95255.8767 10364.9260.021110382.73269.221110413.43274.7212
10433.87 286.34210444.09290.388610556.39308.474910586.82309.355710630.58305.6872
#Mann= 3 , 0 , 0
9770.348  0.0562       09770.348  0.0562       010630.58  0.0562       0
#XS Ineff= 2 , 0
       0                               0
Bank Sta=9770.348,10630.58
Exp/Cntr=0.3,0.1

Type RM Length L Ch R = 1 ,24762.23,249.234900,249.234900,249.234900
XS GIS Cut Line= 6
582733.617013455733123.289172475582645.525922116733158.713241773
582473.340991242733211.424173031582342.374669063733259.325859289
582170.067202289733286.206831802581902.775390781733305.525854696
#Sta/Elev= 30
9679.373224.46219699.438224.28879710.217219.76459742.552201.8272 9753.33198.4017
9921.537 193.3559942.329189.45729974.412174.87999996.181172.844310007.03172.9284
10014.31174.833610028.67181.705910039.27184.126210070.72184.151310111.89196.9443
 10132.3206.715510152.66214.329410172.89218.215610193.12218.9915 10223.4229.8465
10233.47230.899210263.68229.688710313.88232.172110343.99235.308310364.06 241.379
10384.13 250.11210414.24259.198810464.32282.094210474.33284.836810536.66289.0752
#Mann= 3 , 0 , 0
9679.373   0.048       09679.373   0.048       010536.66   0.048       0
#XS Ineff= 2 , 0
       0                               0
Bank Sta=9679.373,10536.66
Exp/Cntr=0.3,0.1

Type RM Length L Ch R = 1 ,24512.99,249.234900,249.234900,249.234900
XS GIS Cut Line= 6
582728.372692966732980.224919316582550.539942409732984.976623214
582442.630474017732997.291497402582392.933059307 732997.93993512
582317.562455395732990.874545712582072.547581203732958.854897047
#Sta/Elev= 30
9742.137233.78159745.511232.79579755.515 224.9269765.518218.99839785.525219.3219
9795.529215.14699805.532205.85279815.536198.32639845.547197.0232 9855.55195.9236
9895.564187.99569965.772182.07769985.962172.60889996.057169.737310026.29172.8668
10046.31184.534410056.31186.167310096.39189.207610106.43194.867410136.56205.7282
10156.66209.432510176.84  211.6710197.01217.400810237.36222.758410257.54226.6704
10267.63231.801910277.72234.427310307.98234.147710348.33240.730110401.18242.4107
#Mann= 3 , 0 , 0
9742.137    0.06       09742.137    0.06       010401.18    0.06       0
#XS Ineff= 2 , 0
       0                               0
Bank Sta=9742.137,10401.18
Exp/Cntr=0.3,0.1

Type RM Length L Ch R = 1 ,24263.76,249.234900,249.234900,249.234900
XS GIS Cut Line= 6
582784.898449548732876.166140148582717.074746379732863.101106062
 582625.30942221732828.774435218582406.055943522732681.389219592
582351.374564437732654.442656971582222.057812177 732606.66401439
#Sta/Elev= 30
9704.608234.87879724.674231.91319745.133227.52629755.377224.5224 9765.62 218.621
9775.921214.73069796.955215.09339807.472211.06439828.505206.75269839.386201.6859
9850.315 193.4259861.245183.00269871.836179.98239930.345178.55779954.681179.1889
9967.292174.31099979.904167.92969987.738166.358510004.18166.035810030.27177.6683
10090.04182.2931 10102.8186.620810137.61188.1239 10182.2192.378810193.35 192.056
10204.25189.383910215.02193.124210225.78198.689710300.72204.585410335.32210.4031
#Mann= 3 , 0 , 0
9704.608  0.0742       09704.608  0.0742       010335.32  0.0742       0
#XS Ineff= 2 , 0
       0                               0
Bank Sta=9704.608,10335.32
Exp/Cntr=0.3,0.1

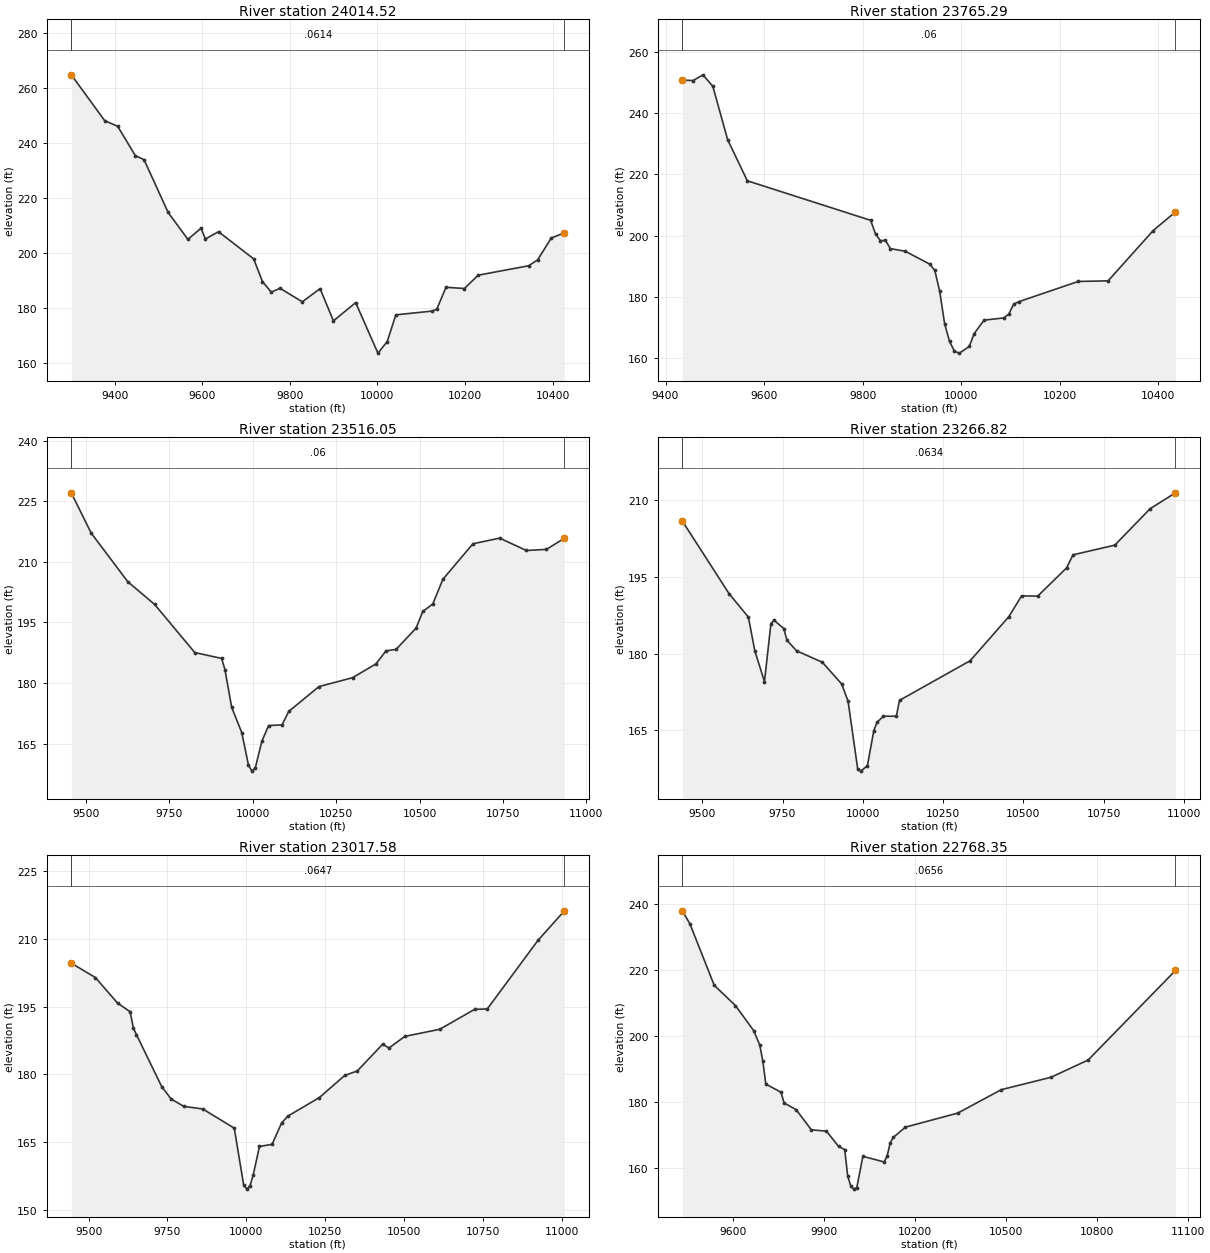
Type RM Length L Ch R = 1 ,24014.52,249.234900,249.234900,249.234900
XS GIS Cut Line= 6
583350.603037002732596.721546935583130.122309903732612.689035566
583011.476109503732611.386839813582856.192522509732595.595531595
582625.224593461732553.233880884582245.887515889732441.257835713
#Sta/Elev= 30
9300.712264.8576  9376.7248.20629406.795246.04549446.871235.42519466.894233.9285
9521.834214.69839566.959204.89759596.961208.93069606.962205.03799636.964207.6775
9717.203197.78559737.308189.51979757.481185.65889777.654187.06269828.327182.1235
9868.982186.92439899.473175.18279950.292 181.84310001.11163.424310022.22167.5951
10042.01 177.37510125.01178.751310135.52179.393110156.55187.427910198.61186.9744
10230.15191.831910345.27195.263610365.95197.407510396.99205.3645 10427.1207.2952
#Mann= 3 , 0 , 0
9300.712  0.0614       09300.712  0.0614       0 10427.1  0.0614       0
#XS Ineff= 2 , 0
       09959.437                       0
Bank Sta=9300.712,10427.1
Exp/Cntr=0.3,0.1

Type RM Length L Ch R = 1 ,23765.29,249.234900,249.234900,249.234900
XS GIS Cut Line= 6
583236.791979274732331.162412315583105.707044766732329.056792923
582642.677658678732309.695191653582543.430706717732302.617885137
582423.696851927732287.739354806582240.081489707732258.597409093
#Sta/Elev= 30
9434.143250.72829455.938250.57299475.941252.44269495.943   248.79525.947231.3116
9565.953 217.8859816.175204.99269826.184200.52079836.193198.33129846.201198.4776
 9856.21195.75669886.237194.92039936.281190.6955 9946.29188.69129956.299181.8903
9966.308 171.3129976.317165.49389986.326162.27819996.335161.680910016.35163.8527
10026.36168.0615 10046.4172.4387 10086.5173.161310096.53 174.40810106.55177.6511
10116.58178.447110237.44185.053610298.14185.254910389.27201.608210434.75207.7428
#Mann= 3 , 0 , 0
9434.143    0.06       09434.143    0.06       010434.75    0.06       0
#XS Ineff= 2 , 0
       0                               0
Bank Sta=9434.143,10434.75
Exp/Cntr=0.3,0.1

Type RM Length L Ch R = 1 ,23516.05,249.234800,249.234800,249.234800
XS GIS Cut Line= 6
 583234.33910521732102.797807068582896.962712178732083.671568852
582565.159385961732047.354678726582214.500314113732015.770162388
582009.540106187732003.335286892581761.051302344731995.065227337
#Sta/Elev= 30
 9456.44227.09619515.836217.13879625.971205.05379706.147199.4539 9826.48187.5257
9906.825186.08029916.881 183.2989937.018173.96059967.223167.71459987.361159.6504
9997.429158.1568 10007.5158.854510027.64165.602110047.78169.438110088.07 169.612
10108.21172.963410198.69179.095310299.18181.293410369.41184.714410399.51187.9514
10429.61 188.303 10489.8193.588310509.83197.705910539.89199.577210569.94205.6629
10660.11214.4803 10740.2 215.87510820.25212.811610880.29213.087610934.25215.8422
#Mann= 3 , 0 , 0
 9456.44    0.06       0 9456.44    0.06       010934.25    0.06       0
#XS Ineff= 2 , 0
       0                               0
Bank Sta=9456.44,10934.25
Exp/Cntr=0.3,0.1

Type RM Length L Ch R = 1 ,23266.82,249.234900,249.234900,249.234900
XS GIS Cut Line= 6
583280.191424563731845.695506615582734.477549317731815.248436327
582445.897129121731805.592069819582283.109602869731803.738331219
582094.328042441731805.687809951 581746.23790468731816.208024228
#Sta/Elev= 30
9438.229205.83539583.666191.68219643.767187.10969663.801180.53499693.851 174.525
9713.885185.84559723.902186.49479753.953184.8791 9763.97182.5767 9794.02180.5333
9874.141 178.2969934.213174.07349954.237170.67929984.273157.40619994.278157.0635
10014.29158.1339 10034.3164.9675 10044.3166.594610064.32 167.77410104.34167.7748
10114.34170.873710334.44178.611310454.45187.183110494.45191.258110544.45 191.205
10634.46 196.71410654.47199.262110784.51201.149910894.57 208.26410973.38211.3584
#Mann= 3 , 0 , 0
9438.229  0.0634       09438.229  0.0634       010973.38  0.0634       0
#XS Ineff= 2 , 0
       09854.926                       0
Bank Sta=9438.229,10973.38
Exp/Cntr=0.3,0.1

Type RM Length L Ch R = 1 ,23017.58,249.234900,249.234900,249.234900
XS GIS Cut Line= 6
583271.232290518731587.976779333 582871.20506106731568.101083775
582712.649822773 731565.54230086582529.872617745731568.636734971
582353.551475515731579.492067708581711.794929341731646.453360042
#Sta/Elev= 30
9445.269204.57119521.677201.39589591.787195.7714 9631.85193.85699641.866 190.314
9651.882188.78749731.956177.32659761.975174.58619802.001172.96199862.032172.3958
9962.045168.15219992.048155.556910002.05154.696310012.05155.470210022.05157.8089
10042.06164.118910082.06164.582910112.07 169.28810132.07 170.81610232.16174.9161
10312.31 179.78410352.39180.788610432.72186.687110452.82185.848910503.05188.4156
10613.67189.974310724.32194.376110764.56194.471910925.51 209.62411009.11216.1255
#Mann= 3 , 0 , 0
9445.269  0.0647       09445.269  0.0647       011009.11  0.0647       0
#XS Ineff= 2 , 0
       0                               0
Bank Sta=9445.269,11009.11
Exp/Cntr=0.3,0.1

Type RM Length L Ch R = 1 ,22768.35,249.234900,249.234900,249.234900
XS GIS Cut Line= 6
583289.607157849731332.770288696582968.057008364731315.654258208
582605.815302358731321.491349681582474.711867333731338.407446051
581897.688988715731461.816768654581681.772742704 731498.48686875
#Sta/Elev= 30
9432.096237.86979456.817 233.9469537.141215.28629607.237 209.1229667.289201.5196
9687.293197.15239697.295192.32869707.297185.28629757.306182.84449767.306179.5937
9807.306177.54759857.306171.43249907.306171.03179947.306166.37239967.306  165.45
9977.306157.40779987.307 154.4149997.308153.439510007.31153.904710027.32 163.399
 10097.4 161.68110107.42163.474610117.44167.5195 10127.5169.111710167.74172.2501
10340.21176.503510483.59183.612310647.61187.374510770.22192.616711057.98219.7802
#Mann= 3 , 0 , 0
9432.096  0.0656       09432.096  0.0656       011057.98  0.0656       0
#XS Ineff= 2 , 0
       0                               0
Bank Sta=9432.096,11057.98
Exp/Cntr=0.3,0.1