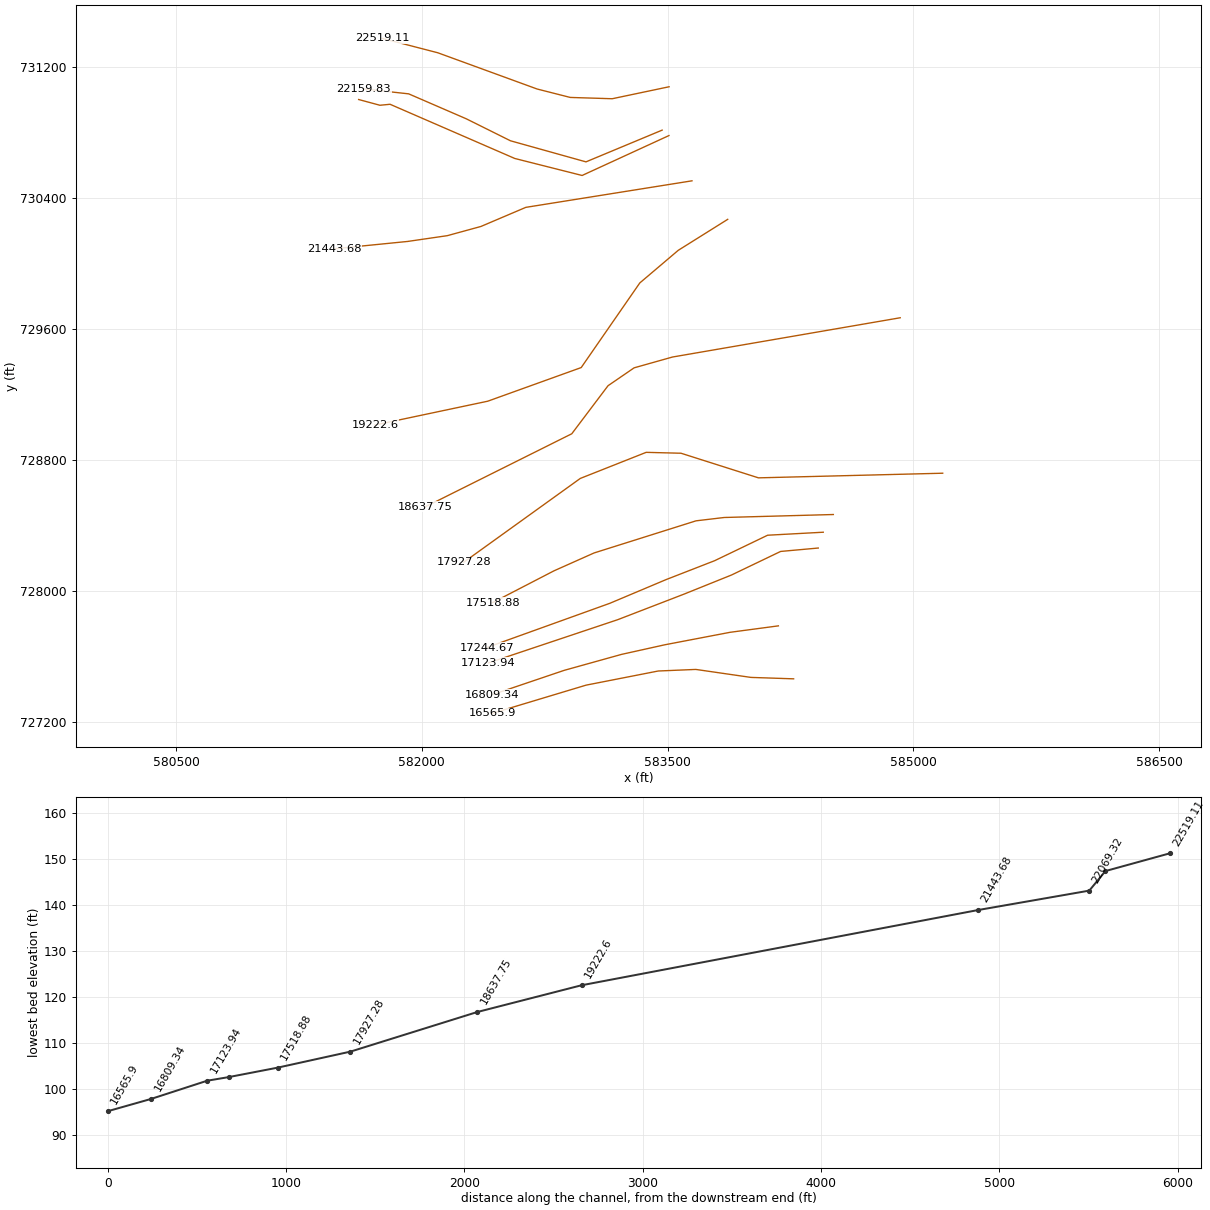
HEC-RAS study 2351_ras.prj: 2351

--- 2351_ras.g01 (geometry) --- (continued)

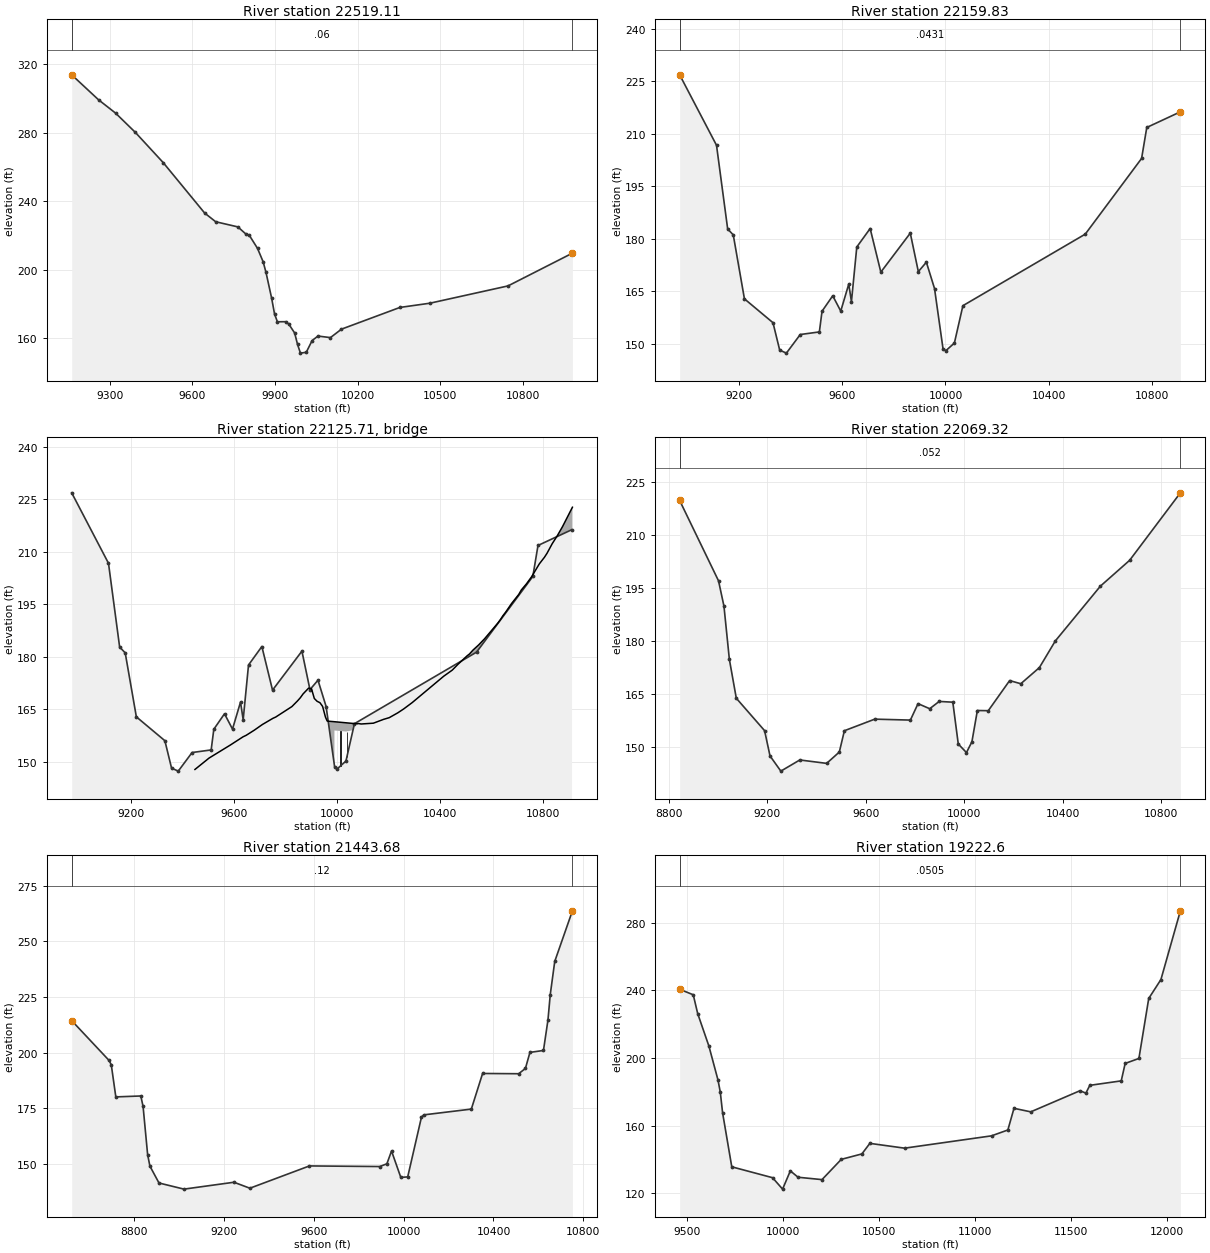
Type RM Length L Ch R = 1 ,22519.11,359.280800,359.280800,359.280800
XS GIS Cut Line= 6
583509.441232533731079.005902065583162.190752926731005.931477287
 582906.10392801 731013.82229067582703.648685591731065.322973603
582097.699507992 731286.45409487 581757.73429785731374.604283038
#Sta/Elev= 30
9162.113   313.89259.716299.18689321.534291.40059393.109280.16329494.321262.4868
9644.716 233.0179684.776 227.9249765.334224.9092 9795.83220.5408 9806.03220.2212
9836.631212.36169857.178204.49179867.508198.27879888.168183.05919898.498173.9902
9908.828169.45659940.147169.49459950.601167.97219971.509162.90439981.963156.2187
9992.504151.127310013.66151.622310034.85158.455610056.03 161.10510101.36160.2023
10141.55165.145410353.61177.833610462.34180.303910745.98190.411110979.86209.5709
#Mann= 3 , 0 , 0
9162.113    0.06       09162.113    0.06       010979.86    0.06       0
#XS Ineff= 2 , 0
       0                               0
Bank Sta=9162.113,10979.86
Exp/Cntr=0.3,0.1

Type RM Length L Ch R = 1 ,22159.83,90.516300,90.516300,90.516300
XS GIS Cut Line= 6
583467.015905023730814.306698307583001.980939984730620.542129532
582541.098072857730749.257164493582271.211709231730883.508329988
581919.667420238731035.751919731581645.449762227731065.841948848
#Sta/Elev= 30
8968.472226.87059111.489206.73049154.822182.77659176.489181.10789219.822162.8142
9330.669155.99039356.669148.15329382.669147.29289436.489152.61349510.622153.3549
9520.995159.2736 9562.49163.6914 9593.61159.31269624.731167.03759635.104162.0014
9655.851177.63399707.719182.92129749.213170.45659863.492181.60269894.705170.6005
9925.917173.29029957.502165.77149990.552148.524610001.57147.995610034.62150.1724
10067.67160.857310542.51181.318110761.15202.963510781.24211.819210911.64216.2909
#Mann= 3 , 0 , 0
8968.472  0.0431       08968.472  0.0431       010911.64  0.0431       0
#XS Ineff= 2 , 0
       09925.392         10088.3       0
Bank Sta=8968.472,10911.64
Exp/Cntr=0.3,0.1

Type RM Length L Ch R = 3 ,22125.71,,,
BEGIN DESCRIPTION:
END DESCRIPTION:
Bridge Culvert--1,0,-1,-1, 0
Deck Dist Width WeirC Skew NumUp NumDn MinLoCord MaxHiCord MaxSubmerge Is_Ogee
33.258150,24.000000,2.6,0, 60, 60, , , 0.95, 0, 0,0,,
 9447.59 9502.50 9584.89 9634.49 9647.11 9678.24 9709.46 9750.87 9761.24 9824.49
 9846.28 9857.18 9868.07 9889.86 9891.52 9900.76 9911.65 9922.55 9933.44 9942.35
 9944.22 9954.91 9961.76 9989.87 9989.8710061.8710061.8710078.9010083.1110093.79
10141.2210180.6310202.9110236.3210258.6010292.0210414.8410447.9610470.2410505.65
10514.8010528.3510551.0510573.7510624.2510634.6510645.0510655.4610678.4610706.35
10716.3510736.3510756.3610786.3610806.3610816.3610836.3610856.3710876.3710915.05
  147.77  151.03  154.74  157.10  157.55  159.00  160.61  162.40  162.74  165.75
  167.37  168.27  169.38  171.05  170.94  170.83  168.06  167.26  166.86  165.96
  165.71  162.75  161.60  161.42  161.42  160.93  160.93  160.82  160.90  160.77
  161.00  162.09  162.58  163.97  165.05  166.88  174.44  176.18  177.85  180.26
  180.79  181.89  183.42  185.16  189.55  190.57  191.75  192.74  195.22  197.81
  199.09  200.84  202.87  206.55  208.45  209.59  212.31  214.61  217.18  222.75
 -852.23 -848.97 -845.26 -842.90 -842.45 -841.00 -839.39 -837.60 -837.26 -834.25
 -832.63 -831.73 -830.62 -828.95 -829.06 -829.17 -831.94 -832.74 -833.14 -834.04
 -834.29 -837.25 -838.40 -838.58  158.92  158.43 -839.07 -839.18 -839.10 -839.23
 -839.00 -837.91 -837.42 -836.03 -834.95 -833.12 -825.56 -823.82 -822.15 -819.74
 -819.21 -818.11 -816.58 -814.84 -810.45 -809.43 -808.25 -807.26 -804.78 -802.19
 -800.91 -799.16 -797.13 -793.45 -791.55 -790.41 -787.69 -785.39 -782.82 -777.25
 9447.59 9502.50 9584.89 9634.49 9647.11 9678.24 9709.46 9750.87 9761.24 9824.49
 9846.28 9857.18 9868.07 9889.86 9891.52 9900.76 9911.65 9922.55 9933.44 9942.35
 9944.22 9954.91 9961.76 9972.76 9972.7610044.7610044.7610093.7910136.5310180.63
10191.7710210.5310258.6010292.0210414.8410447.9610470.2410505.6510514.8010528.35
10551.0510573.7510592.7710624.2510634.6510645.0510655.4610678.4610706.3510716.35
10736.3510756.3610776.3610786.3610806.3610816.3610836.3610856.3710876.3710915.05
  147.77  151.03  154.74  157.10  157.55  159.00  160.61  162.40  162.74  165.75
  167.37  168.27  169.38  171.05  170.94  170.83  168.06  167.26  166.86  165.96
  165.71  162.75  161.60  161.53  161.53  161.05  161.05  160.77  160.93  162.09
  162.27  162.86  165.05  166.88  174.44  176.18  177.85  180.26  180.79  181.89
  183.42  185.16  186.74  189.55  190.57  191.75  192.74  195.22  197.81  199.09
  200.84  202.87  205.25  206.55  208.45  209.59  212.31  214.61  217.18  222.75
 -852.23 -848.97 -845.26 -842.90 -842.45 -841.00 -839.39 -837.60 -837.26 -834.25
 -832.63 -831.73 -830.62 -828.95 -829.06 -829.17 -831.94 -832.74 -833.14 -834.04
 -834.29 -837.25 -838.40 -838.47  159.03  158.55 -838.95 -839.23 -839.07 -837.91
 -837.73 -837.14 -834.95 -833.12 -825.56 -823.82 -822.15 -819.74 -819.21 -818.11
 -816.58 -814.84 -813.26 -810.45 -809.43 -808.25 -807.26 -804.78 -802.19 -800.91
 -799.16 -797.13 -794.75 -793.45 -791.55 -790.41 -787.69 -785.39 -782.82 -777.25
Pier Skew, UpSta & Num, DnSta & Num=  ,10013.54, 2 ,9996.43, 2 , 0 , 0 , 0 ,,
    2.00    2.00
 -838.74  161.26
    2.00    2.00
 -838.63  161.37
Pier Skew, UpSta & Num, DnSta & Num=  ,10038.20, 2 ,10021.10, 2 , 0 , 0 , 0 ,,
    2.00    2.00
 -838.91  161.09
    2.00    2.00
 -838.80  161.20
BR Coef=-1 , 0 , 0 ,, 0 ,,,0.8,0,1,0,
WSPro=,,,, 1 ,,,, 0 ,,,, 0 ,,,,-1 ,-1 ,-1 , 0 , 0 , 0 , 0 , 0
BC Design=,, 0 ,, 0 ,,,,,,

Type RM Length L Ch R = 1 ,22069.32,625.634800,625.634800,625.634800
XS GIS Cut Line= 6
 583508.53688404730781.089915082582978.452385277730537.500171483
582567.394692898730641.302619055581806.176744193730972.086418569
581744.211523026730966.070377707581614.544737281731001.134552877
#Sta/Elev= 30
8843.293 219.842 9001.26197.02929023.271189.84989045.281 174.728 9073.42163.7235
 9188.35154.52739210.361147.35719254.382143.04059331.419146.2074 9440.51 145.241
9491.961148.45919512.541154.50619636.022157.79239780.704157.52229811.744162.1895
9859.229160.7506 9897.64162.81649953.056162.60649975.222150.735910008.47148.3025
10030.64151.3632 10052.8160.244310097.14 160.18910183.92168.735110229.26167.8425
10304.76172.417510369.48179.980810552.85195.5464 10671.5202.868810877.61 222.014
#Mann= 3 , 0 , 0
8843.293   0.052       08843.293   0.052       010877.61   0.052       0
#XS Ineff= 2 , 0
       09923.771        10079.27       0
Bank Sta=8843.293,10877.61
Exp/Cntr=0.3,0.1

Type RM Length L Ch R = 1 ,21443.68,2221.077800,2221.077800,2221.077800
XS GIS Cut Line= 6
583649.180095017730504.866138861          582635730342.901157737
582360.789238246730226.251812133582155.533860927730170.079851739
581913.193502532730134.761832974581466.659278916 730090.14199544
#Sta/Elev= 30
8520.103214.42868686.364196.59088696.491  194.628716.744180.19598828.138180.6111
8838.265175.90078858.518154.28728868.645149.14928909.152  141.569020.546138.8071
9243.334141.89569314.221139.21469579.737149.21899893.335148.9463 9924.92150.1809
9945.651155.91519987.017144.061810017.76144.298110079.02171.1005 10089.2  172.13
10301.31174.725210351.55190.711810512.29190.596710542.43192.973510562.53200.1722
10622.81201.038810642.92214.735810652.98 226.00510673.09240.996910751.89263.7047
#Mann= 3 , 0 , 0
8520.103    0.12       08520.103    0.12       010751.89    0.12       0
#XS Ineff= 2 , 0
       09860.285                       0
Bank Sta=8520.103,10751.89
Exp/Cntr=0.3,0.1

Type RM Length L Ch R = 1 , 19222.6,584.857800,584.857800,584.857800
XS GIS Cut Line= 6
583867.173316115730269.706506669583565.422904303730080.698991872
583330.528882115729881.408776673582972.967579395729365.000000015
 582402.23953557729159.586418584581713.865409672729014.044460535
#Sta/Elev= 30
9463.453240.65999534.156237.4138 9557.43226.23729615.614207.07789662.998 186.972
9674.932179.80629686.867167.59449734.678135.66729946.953129.23189999.084122.4751
10039.42133.264710079.71129.500310204.18128.097210304.58140.082210411.87143.2971
10453.26 149.53710634.07146.699911086.45153.987511171.47157.450811203.35170.2699
11290.66168.177311546.86180.675211577.53179.239911597.97183.856211761.51186.4971
11781.95196.8117 11853.5199.7574 11904.6235.242311967.99246.4099 12069.3 287.062
#Mann= 3 , 0 , 0
9463.453  0.0505       09463.453  0.0505       0 12069.3  0.0505       0
#XS Ineff= 2 , 0
       0                10466.17       0
Bank Sta=9463.453,12069.3
Exp/Cntr=0.3,0.1

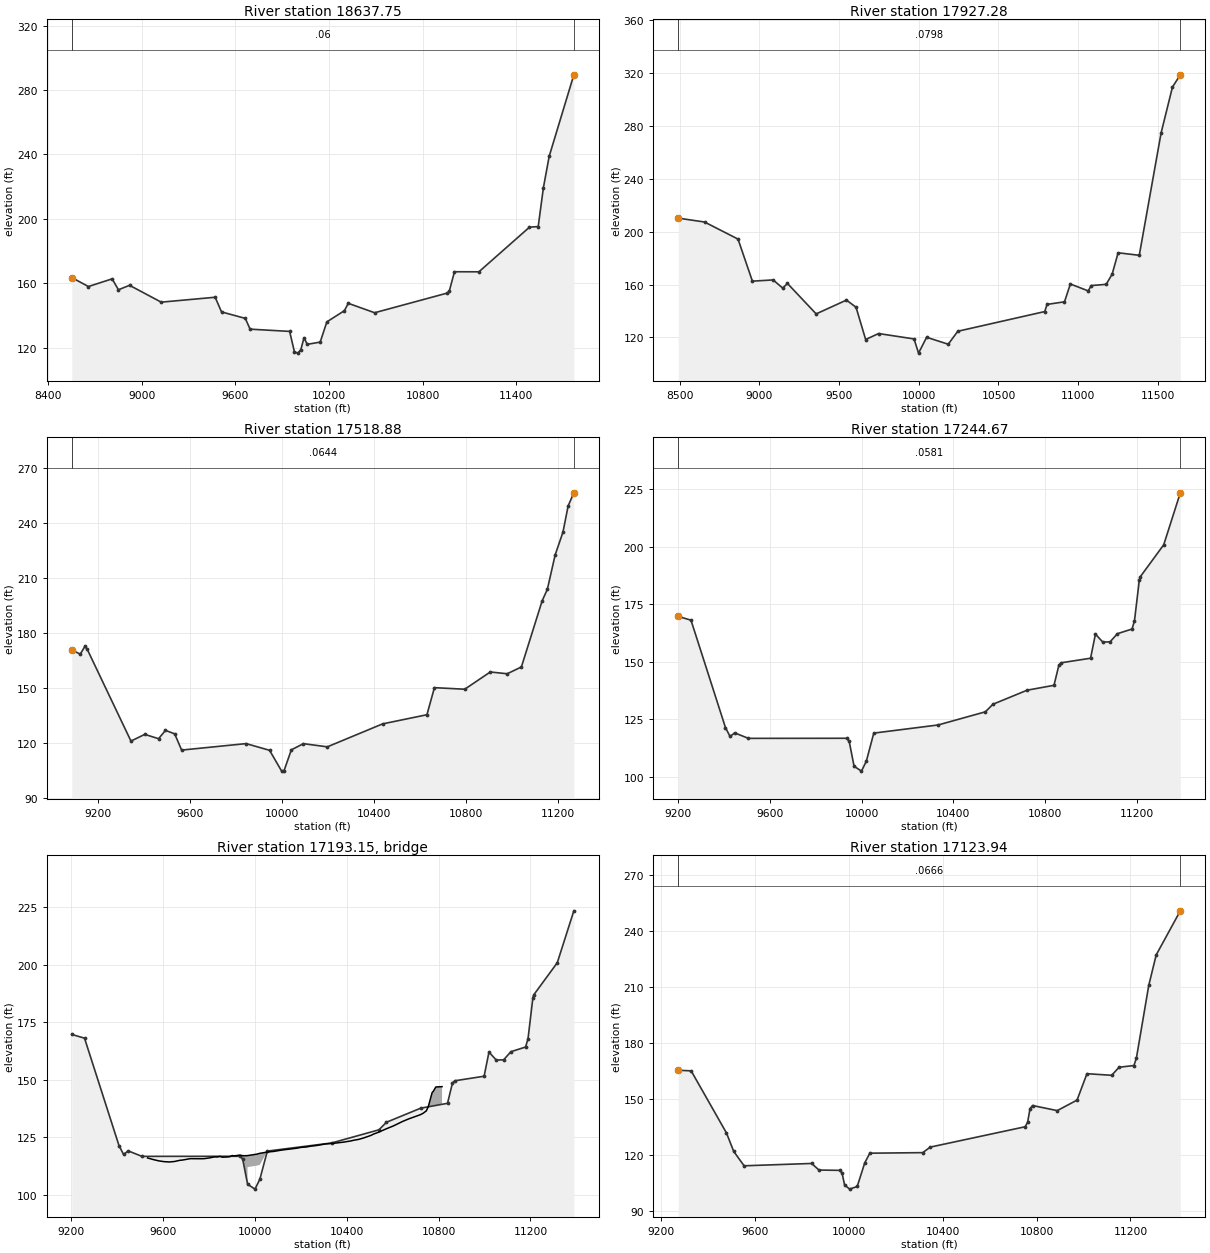
Type RM Length L Ch R = 1 ,18637.75,710.468200,710.468200,710.468200
XS GIS Cut Line= 6
584920.287154282729668.978551961583530.189643756729429.292161062
583296.010640684729363.340967223 583136.73835943729254.170762947
582915.348197324728960.821945739582020.683591515728514.481523484
#Sta/Elev= 30
8551.483163.55758658.026158.00468809.952 162.7588850.533155.9882 8921.55158.7618
9124.455148.30519470.113151.34659510.781142.25459663.282138.21479693.745131.5381
9947.149130.14879977.692 117.5119998.142116.659710018.68118.730210039.22126.2253
10059.83 122.12110142.92123.501810185.48136.045210298.12143.026310322.69  147.58
10491.69141.735710958.35153.980210969.53155.041111003.05167.181111159.51167.1396
 11483.6194.851411539.47195.2328   11573219.448511609.84238.8468 11767.8289.4261
#Mann= 3 , 0 , 0
8551.483    0.06       08551.483    0.06       0 11767.8    0.06       0
#XS Ineff= 2 , 0
       0                               0
Bank Sta=8551.483,11767.8
Exp/Cntr=0.3,0.1

Type RM Length L Ch R = 1 ,17927.28,408.396800,408.396800,408.396800
XS GIS Cut Line= 6
585179.667024497728720.027807306584054.831131613728691.757029619
583582.070779969728842.001285182583369.425452288728847.409245926
582967.439654857728688.257301778582257.128720867728177.432851099
#Sta/Elev= 30
8490.418210.22278655.391207.29948865.684194.36228955.799162.52589085.911163.4666
9145.949 157.2839175.961160.78319355.993137.75489546.097148.20239606.212142.7835
9666.587118.36089747.669122.88369970.337 118.7949998.545108.0602 10049.2120.0538
 10184.7 114.79710244.82124.609710790.42139.518310804.83144.932910914.44146.9056
10951.24160.3835 11063.3155.155511082.51159.200911175.91160.119211213.45167.8068
11250.99184.010111383.71182.102311520.75274.764811592.09309.486111641.25318.6985
#Mann= 3 , 0 , 0
8490.418  0.0798       08490.418  0.0798       011641.25  0.0798       0
#XS Ineff= 2 , 0
       09740.746                       0
Bank Sta=8490.418,11641.25
Exp/Cntr=0.3,0.1

Type RM Length L Ch R = 1 ,17518.88,274.214600,274.214600,274.214600
XS GIS Cut Line= 6
584512.019394304728467.911237654583845.802793247728449.767216579
583673.897850738728429.399585079583051.744517548728233.438723453
582806.439380686728124.020138194 582433.04457713727930.806410839
#Sta/Elev= 30
9087.408170.58899124.456168.37629144.472 172.6179154.479171.04529344.571120.9595
9404.588124.61369464.606122.25729494.614 126.7999534.626124.89569564.634116.0466
9844.935119.57969946.847115.92059999.295104.573110009.87104.873710041.49116.1775
10093.96119.551510197.77 117.81610437.82130.329310630.57135.325210663.13150.0921
 10794.9149.2269 10905.9158.644710979.36157.665411041.02161.3739 11131.3197.4535
11153.87203.738511187.73222.472211221.58234.857811244.15249.191611268.93 256.328
#Mann= 3 , 0 , 0
9087.408  0.0644       09087.408  0.0644       011268.93  0.0644       0
#XS Ineff= 2 , 0
       09532.397                       0
Bank Sta=9087.408,11268.93
Exp/Cntr=0.3,0.1

Type RM Length L Ch R = 1 ,17244.67,120.725900,120.725900,120.725900
XS GIS Cut Line= 6
 584450.47549051728359.856111169584110.785681397728341.527524352
583788.202553332728186.345489234583490.057541013728070.264439374
583147.923920333727926.079556361582397.067624152727655.980649352
#Sta/Elev= 30
9201.507169.74869257.063168.11419407.281121.4342 9427.31117.57339447.339  119.14
9507.426116.75869935.419116.79999946.151115.53879967.613104.64179999.807102.5226
10021.27106.910310053.46119.040410333.74122.579110539.92128.303210572.48131.5767
10721.64137.693610838.54139.811710860.09148.617710870.43149.606610997.95151.5847
11019.21162.065311051.09158.609511082.97158.708811114.86162.244711178.62 164.266
11189.25167.7996 11210.5185.669311214.61186.986211316.77200.893611388.97223.4545
#Mann= 3 , 0 , 0
9201.507  0.0581       09201.507  0.0581       011388.97  0.0581       0
#XS Ineff= 2 , 0
       09547.819                       0
Bank Sta=9201.507,11388.97
Exp/Cntr=0.3,0.1

Type RM Length L Ch R = 3 ,17193.15,,,
BEGIN DESCRIPTION:
END DESCRIPTION:
Bridge Culvert--1,0,-1,-1, 0
Deck Dist Width WeirC Skew NumUp NumDn MinLoCord MaxHiCord MaxSubmerge Is_Ogee
30.362950,60.000000,2.6,0, 60, 60, , , 0.95, 0, 0,0,,
 9531.86 9557.44 9580.34 9603.24 9626.14 9649.05 9671.95 9683.40 9717.75 9771.67
 9782.39 9803.83 9823.66 9835.99 9846.71 9857.43 9879.18 9889.59 9900.31 9911.03
 9932.47 9943.19 9953.91 9967.28 9967.2810007.5110018.2310053.2810053.2810082.55
10114.9010179.9910201.6910223.3810245.0810266.7810307.4110342.7110386.1010418.65
10429.5010451.1910472.8910505.4310516.2810537.9810570.5210603.0710642.8010668.60
10720.2010733.2410744.0910746.0010754.9410765.7910771.8010776.6310787.4810814.73
  116.07  115.35  114.81  114.47  114.32  114.53  115.04  115.15  115.76  115.73
  115.81  116.13  116.54  116.49  116.77  116.40  116.50  116.62  117.10  116.99
  117.30  117.08  117.03  117.09  117.09  117.71  118.03  118.63  118.63  118.92
  119.48  120.28  120.67  120.83  121.23  121.46  122.17  122.43  122.95  123.48
  123.75  124.13  124.75  125.88  126.44  127.24  128.68  130.00  131.93  133.01
  134.86  135.54  136.39  136.46  138.41  142.41  144.53  145.03  146.90  147.06
 -883.93 -884.65 -885.19 -885.53 -885.68 -885.47 -884.96 -884.85 -884.24 -884.27
 -884.19 -883.87 -883.46 -883.51 -883.23 -883.60 -883.50 -883.38 -882.90 -883.01
 -882.70 -882.92 -882.97 -882.91  112.09  112.71  113.03  113.63 -881.37 -881.08
 -880.52 -879.72 -879.33 -879.17 -878.77 -878.54 -877.83 -877.57 -877.05 -876.52
 -876.25 -875.87 -875.25 -874.12 -873.56 -872.76 -871.32 -870.00 -868.07 -866.99
 -865.14 -864.46 -863.61 -863.54 -861.59 -857.59 -855.47 -854.97 -853.10 -852.94
 9531.86 9557.44 9580.34 9603.24 9626.14 9649.05 9671.95 9683.40 9717.75 9771.67
 9782.39 9803.83 9823.66 9835.99 9846.71 9851.42 9857.43 9879.18 9889.59 9900.31
 9911.03 9932.47 9943.19 9966.39 9966.3910007.5110018.2310052.3910052.3910082.55
10114.9010179.9910201.6910223.3810245.0810266.7810307.4110342.7110386.1010418.65
10429.5010451.1910472.8910505.4310516.2810537.9810570.5210603.0710642.8010668.60
10720.2010733.2410744.0910746.0010754.9410765.7910771.8010776.6310787.4810814.73
  116.07  115.35  114.81  114.47  114.32  114.53  115.04  115.15  115.76  115.73
  115.81  116.13  116.54  116.49  116.77  116.66  116.40  116.50  116.62  117.10
  116.99  117.30  117.08  117.07  117.07  117.71  118.03  118.63  118.63  118.92
  119.48  120.28  120.67  120.83  121.23  121.46  122.17  122.43  122.95  123.48
  123.75  124.13  124.75  125.88  126.44  127.24  128.68  130.00  131.93  133.01
  134.86  135.54  136.39  136.46  138.41  142.41  144.53  145.03  146.90  147.06
 -883.93 -884.65 -885.19 -885.53 -885.68 -885.47 -884.96 -884.85 -884.24 -884.27
 -884.19 -883.87 -883.46 -883.51 -883.23 -883.34 -883.60 -883.50 -883.38 -882.90
 -883.01 -882.70 -882.92 -882.93  112.07  112.71  113.03  113.63 -881.37 -881.08
 -880.52 -879.72 -879.33 -879.17 -878.77 -878.54 -877.83 -877.57 -877.05 -876.52
 -876.25 -875.87 -875.25 -874.12 -873.56 -872.76 -871.32 -870.00 -868.07 -866.99
 -865.14 -864.46 -863.61 -863.54 -861.59 -857.59 -855.47 -854.97 -853.10 -852.94
BR Coef=-1 , 0 , 0 ,, 0 ,,,0.8,0,1,0,
WSPro=,,,, 1 ,,,, 0 ,,,, 0 ,,,,-1 ,-1 ,-1 , 0 , 0 , 0 , 0 , 0
BC Design=,, 0 ,, 0 ,,,,,,

Type RM Length L Ch R = 1 ,17123.94,314.605100,314.605100,314.605100
XS GIS Cut Line= 6
584419.927845806728263.325553894584190.209557652728242.553155497
583889.620733738728098.368272483583601.250967741727982.287222624
583195.578246057727825.883281738582407.484290838727562.230649352
#Sta/Elev= 30
9272.116165.42599327.268165.0738 9477.88131.7964 9508.55121.97249552.914114.2346
9841.134115.48779871.952 111.9589959.712111.79389970.492110.40359981.271104.0405
10002.83101.735110035.17103.158310067.51115.856810089.07120.987910314.47121.2785
10346.62124.241110751.11135.143510761.66137.4915 10772.2144.897310782.75146.5169
 10888.2143.789610972.55149.431511014.73163.558411120.18162.707311151.82167.0235
11215.08167.937811225.63171.950911278.35210.915611309.99227.190911412.81250.8026
#Mann= 3 , 0 , 0
9272.116  0.0666       09272.116  0.0666       011412.81  0.0666       0
#XS Ineff= 2 , 0
       09553.861                       0
Bank Sta=9272.116,11412.81
Exp/Cntr=0.3,0.1

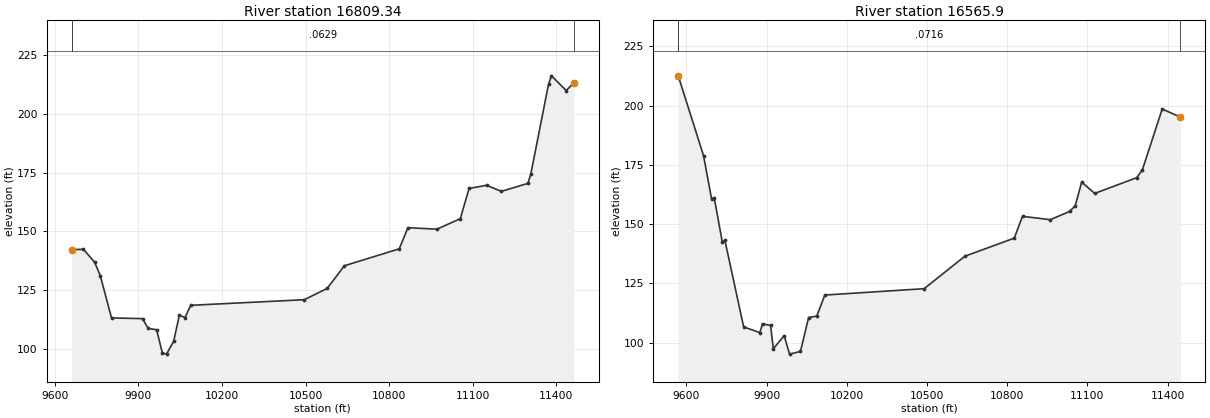
Type RM Length L Ch R = 1 ,16809.34,243.439100,243.439100,243.439100
XS GIS Cut Line= 6
584176.647780634727788.296178066 583881.87850448727748.969811984
583483.716757719727672.852497608583218.126970839727613.913498327
582868.952816257727516.652790852582429.389369201 727367.90438763
#Sta/Elev= 30
 9661.05142.22649702.921  142.379743.204136.84889763.346131.17139803.629113.1875
9914.843112.87379935.095108.74179965.516108.13969985.89298.36553   1000197.77783
10026.63103.226310046.99114.321210067.35113.338910087.71118.542410495.47120.9281
 10577.5125.733110639.18135.369810835.99142.567910867.22151.566910971.33150.9316
11055.13155.398111086.65168.255811149.69169.6021 11202.3167.021111297.54170.4059
11308.13174.371411371.62212.539211382.21216.171911435.25209.915811462.54213.2482
#Mann= 3 , 0 , 0
 9661.05  0.0629       0 9661.05  0.0629       011462.54  0.0629       0
#XS Ineff= 2 , 0
       0                               0
Bank Sta=9661.05,11462.54
Exp/Cntr=0.3,0.1

Type RM Length L Ch R = 1 , 16565.9,243.439200,243.439200,243.439200
XS GIS Cut Line= 6
584269.584751638727464.919889407584008.723163227727473.631030474
  583672.5234853727522.333346742583443.103837313727512.683536922
 583002.94077038727426.448527299582429.905128979727254.063341485
#Sta/Elev= 30
9569.226212.60519663.815178.90579693.817160.70989703.819161.14259733.847142.5325
9743.857143.09149813.998106.59219874.389104.19029884.468 107.8689914.704107.2092
9924.82597.37442  9965.5102.89329985.83895.1041210026.4996.2413910056.97110.5647
10087.39111.130410117.61120.050410489.18 122.72910641.73136.450310826.27144.0769
10857.18153.301810960.77 151.86111033.39  155.3411054.27157.739811078.53167.7444
11127.35162.9674 11284.4169.602911305.43172.874111379.77198.575911447.48195.2196
#Mann= 3 , 0 , 0
9569.226  0.0716       09569.226  0.0716       011447.48  0.0716       0
#XS Ineff= 2 , 0
       0                               0
Bank Sta=9569.226,11447.48
Exp/Cntr=0.3,0.1