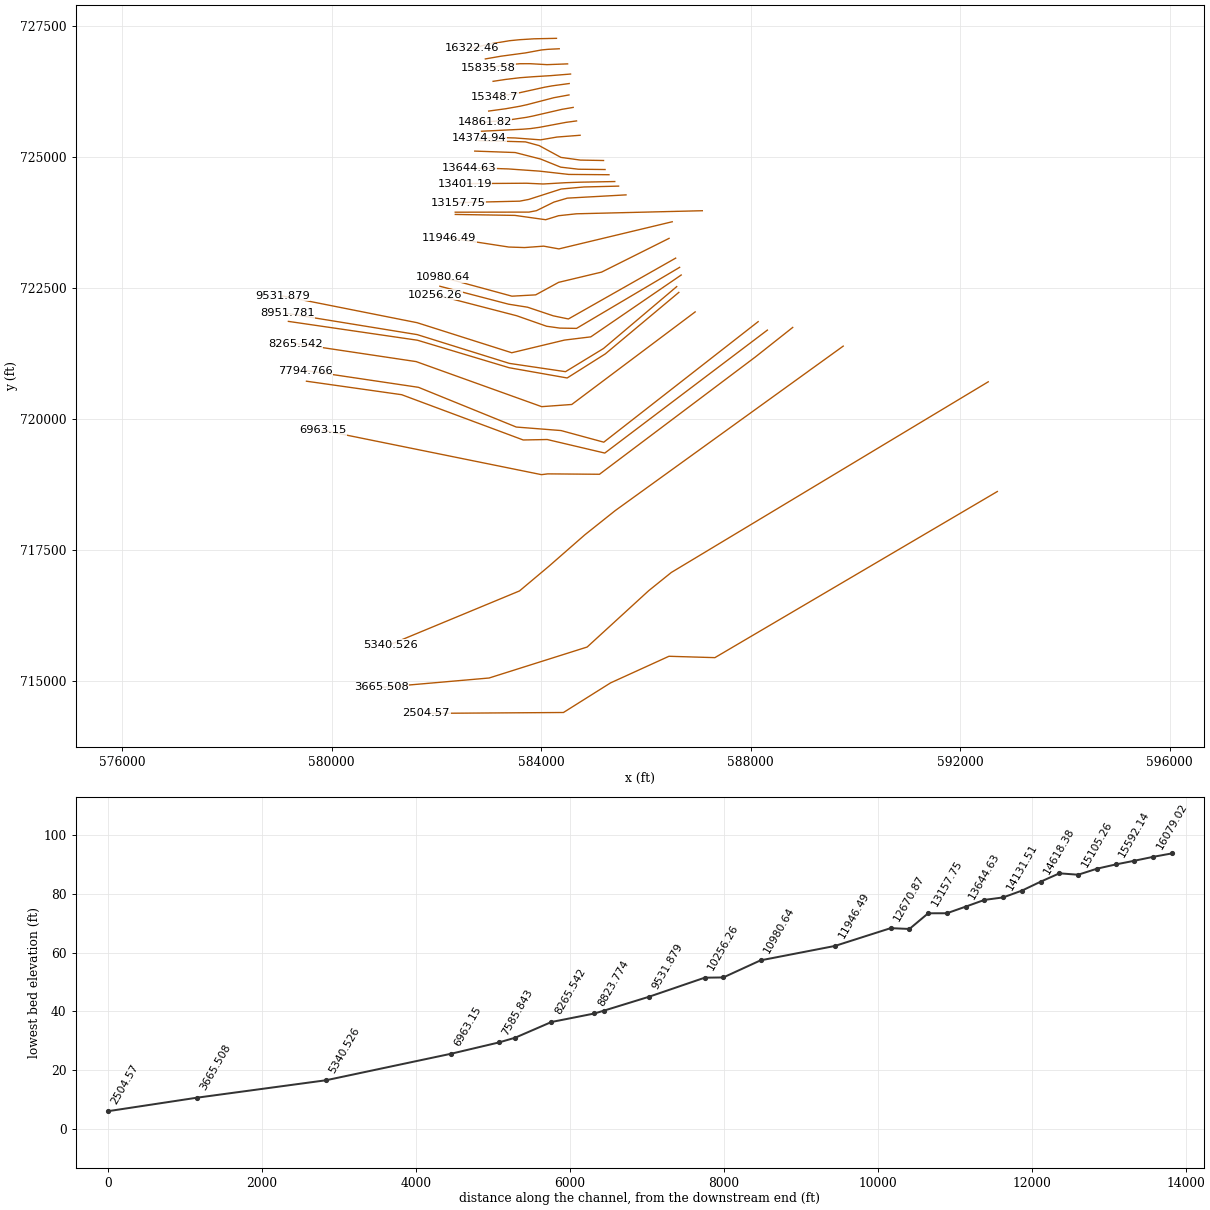
HEC-RAS study 2351_ras.prj: 2351

--- 2351_ras.g01 (geometry) --- (continued)

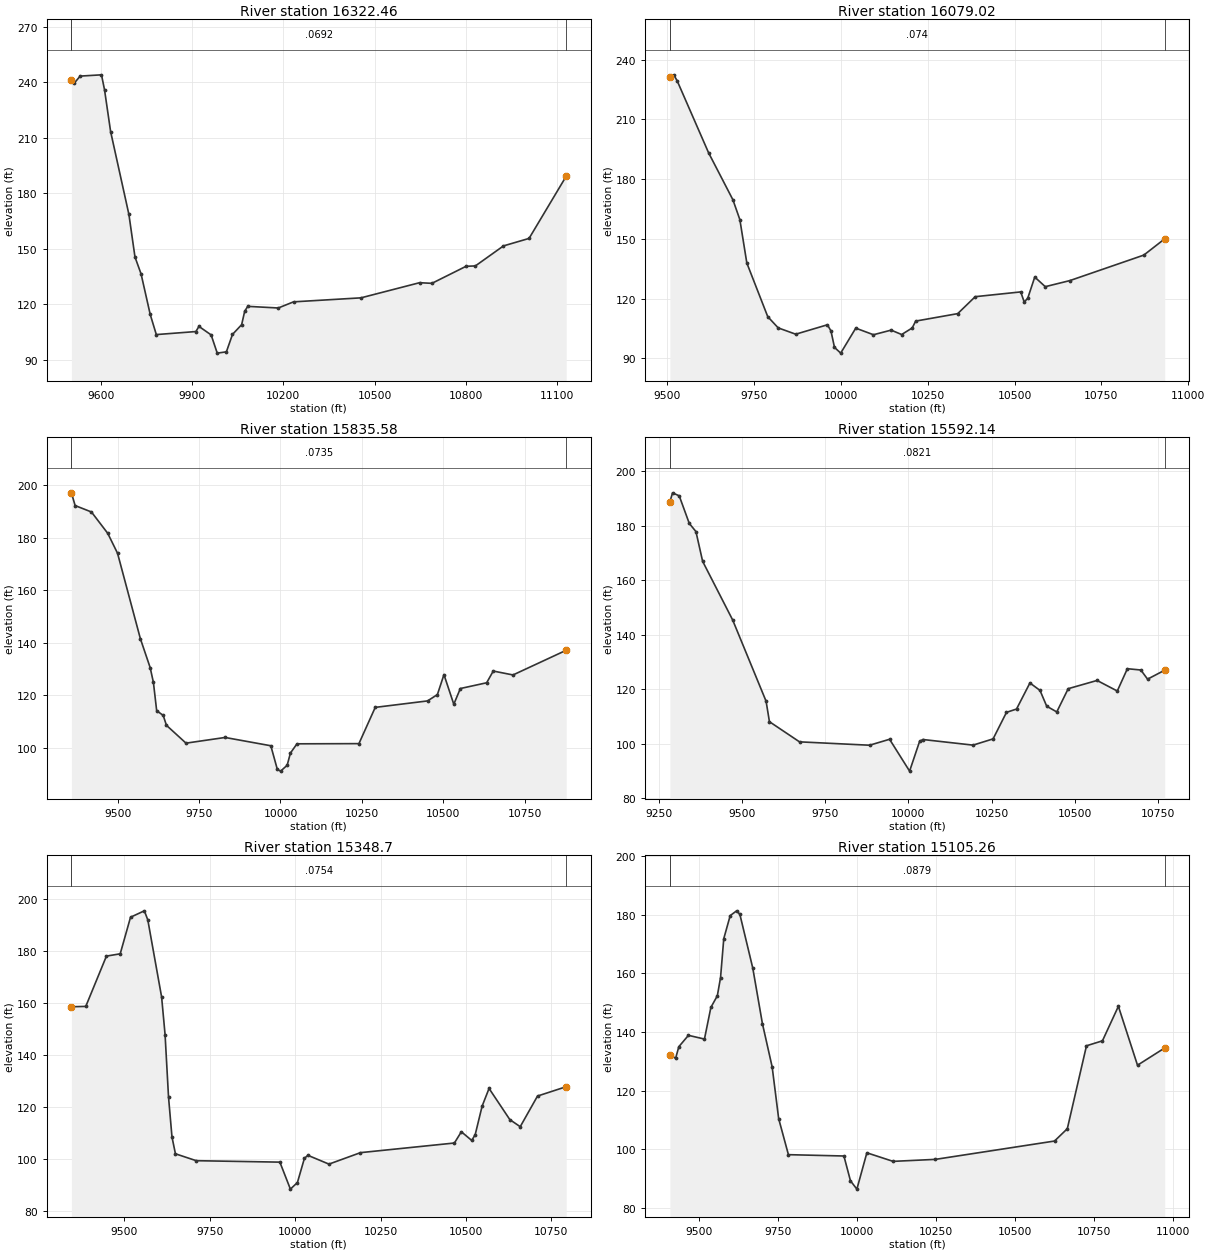
Type RM Length L Ch R = 1 ,16322.46,243.439100,243.439100,243.439100
XS GIS Cut Line= 6
584293.766421919727273.326655617583870.744921884727264.536075461
583593.230255881727247.434139512583400.412441829727228.289341872
 583027.98240625727166.499523339582684.938035739727085.446543631
#Sta/Elev= 30
9504.094241.44769512.862239.42879532.866 243.3529602.881244.03689612.883235.9304
9632.888213.37079692.901168.65119712.905145.62629732.909136.49399762.916114.6288
 9782.92103.74479912.948105.3798 9922.95108.16329962.997103.55859983.02293.72662
10013.07 94.422910033.12103.832610063.18109.0962 10073.2116.332210083.22118.9888
10183.44 118.10710233.59121.421410455.02123.583710647.42131.759410688.11131.4258
10800.17140.622610830.89 140.83210923.06151.640511007.08155.679611129.15189.2885
#Mann= 3 , 0 , 0
9504.094  0.0692       09504.094  0.0692       011129.15  0.0692       0
#XS Ineff= 2 , 0
       0                               0
Bank Sta=9504.094,11129.15
Exp/Cntr=0.3,0.1

Type RM Length L Ch R = 1 ,16079.02,243.439100,243.439100,243.439100
XS GIS Cut Line= 6
584346.299310929727074.254990278584127.221684242727063.220776064
584009.046978474727051.763273528583704.481910839726995.523955535
583231.530728225726931.780255425582935.898578512726880.275420462
#Sta/Elev= 30
9507.025231.27299518.333  232.41 9528.34229.26679618.449193.24759688.552169.6114
9708.581159.63049728.617137.85389788.899110.88379819.039105.24039869.451 102.072
9960.742106.80239970.941103.7183 9981.1495.44289    999992.55972 10042.4105.1152
10093.41101.800110144.21104.119410174.59101.913510204.91105.197910215.01108.6573
10336.07112.410710386.47120.924210517.57123.323310527.67118.198510537.77120.1621
10557.96130.779810588.25125.953510659.03129.008110872.05  141.8210932.25149.9939
#Mann= 3 , 0 , 0
9507.025   0.074       09507.025   0.074       010932.25   0.074       0
#XS Ineff= 2 , 0
       0                               0
Bank Sta=9507.025,10932.25
Exp/Cntr=0.3,0.1

Type RM Length L Ch R = 1 ,15835.58,243.439200,243.439200,243.439200
XS GIS Cut Line= 6
584506.415776751726785.750939098 584113.88800853  726770.9767624
583792.898507654726788.923225963583592.230257313726788.596050033
583284.807131296726758.665935936582993.806358071726713.445865083
#Sta/Elev= 30
9358.316197.02149369.749192.17869419.821 189.7419469.868181.62359499.896174.0564
9569.962 141.5869599.991130.6011    9610124.96289620.009 114.2099640.025112.4162
9650.027108.64679710.037101.86659830.051104.02879970.332100.87789990.40991.86463
10000.4591.2330410020.5193.4665310030.5598.1071110050.62101.613410240.76101.6846
10290.83115.464510451.39117.922410481.59120.331410501.73127.923110531.94116.6562
10552.07122.634610632.81124.820510653.03129.276810713.67127.790710876.99137.1827
#Mann= 3 , 0 , 0
9358.316  0.0735       09358.316  0.0735       010876.99  0.0735       0
#XS Ineff= 2 , 0
       0                               0
Bank Sta=9358.316,10876.99
Exp/Cntr=0.3,0.1

Type RM Length L Ch R = 1 ,15592.14,243.439100,243.439100,243.439100
XS GIS Cut Line= 6
584562.984152594726591.850388108584176.434040331726560.636638456
 583847.44041937 726540.42863795583600.300643178726521.756589155
583318.848912411726488.365353135583084.229852712726452.940082929
#Sta/Elev= 30
9283.578188.80539291.588192.11069311.653190.99579341.751180.89629361.816 177.889
9381.881166.97569472.174145.42649572.499 115.6189582.532108.11449672.823 100.718
 9883.2299.477459943.333101.658510003.45 89.970210033.52100.897610043.54 101.571
10193.9599.5137810254.18101.799110294.41111.544510324.57112.7538 10364.8122.3238
10395.04119.6007 10415.2 113.80510445.45 111.69410479.78120.228610566.51123.2504
10627.15119.372710657.47127.5559 10697.9127.083710718.13 123.72710769.58127.0222
#Mann= 3 , 0 , 0
9283.578  0.0821       09283.578  0.0821       010769.58  0.0821       0
#XS Ineff= 2 , 0
       0                               0
Bank Sta=9283.578,10769.58
Exp/Cntr=0.3,0.1

Type RM Length L Ch R = 1 , 15348.7,243.439100,243.439100,243.439100
XS GIS Cut Line= 6
584536.750382968726410.604098814584215.253133449726366.882619206
 584073.99413014726341.641856063583597.615047279726236.500180686
 583460.88497656726211.081429973583111.969332218 726153.96209746
#Sta/Elev= 30
9344.807158.55519386.843 158.682 9447.33177.99669487.655178.87589517.899 192.931
9558.333195.38269568.443191.89039608.884162.29339618.994147.86849629.104123.8801
9639.214108.55429649.324102.0978 9710.1899.442369955.05598.889919985.85788.52474
10006.3991.0546110026.91  100.3610037.17101.503910098.7398.1286310191.05 102.533
10465.98106.231210486.27110.547510516.69107.221110526.83109.436210547.11120.3916
 10567.4127.180810628.25115.211110658.64112.497810709.25124.2621 10793.3127.8555
#Mann= 3 , 0 , 0
9344.807  0.0754       09344.807  0.0754       0 10793.3  0.0754       0
#XS Ineff= 2 , 0
       0                               0
Bank Sta=9344.807,10793.3
Exp/Cntr=0.3,0.1

Type RM Length L Ch R = 1 ,15105.26,243.439200,243.439200,243.439200
XS GIS Cut Line= 6
  584532.9486158726192.932143548584245.509852471726140.382917296
583735.733912803726007.996808815583601.470233302725978.079267904
583325.769496468725929.439078962582999.656470249725885.091912767
#Sta/Elev= 30
9407.336132.20789425.477131.06799435.612135.01679466.019138.89939516.696137.6256
9537.054148.42439557.435152.36819567.625158.58869577.815171.85119598.196179.7119
9618.576181.33489628.766180.13179669.527 161.8579700.102142.8863 9730.95128.1219
9751.515110.50479782.36298.223569957.97397.768869978.70889.31239    999986.47883
10030.58 98.861210113.5595.9408610247.56 96.622410624.37  102.8710664.84107.0736
10725.47135.336610775.99137.027210826.41148.790910886.92128.713610972.98134.5945
#Mann= 3 , 0 , 0
9407.336  0.0879       09407.336  0.0879       010972.98  0.0879       0
#XS Ineff= 2 , 0
       0                               0
Bank Sta=9407.336,10972.98
Exp/Cntr=0.3,0.1

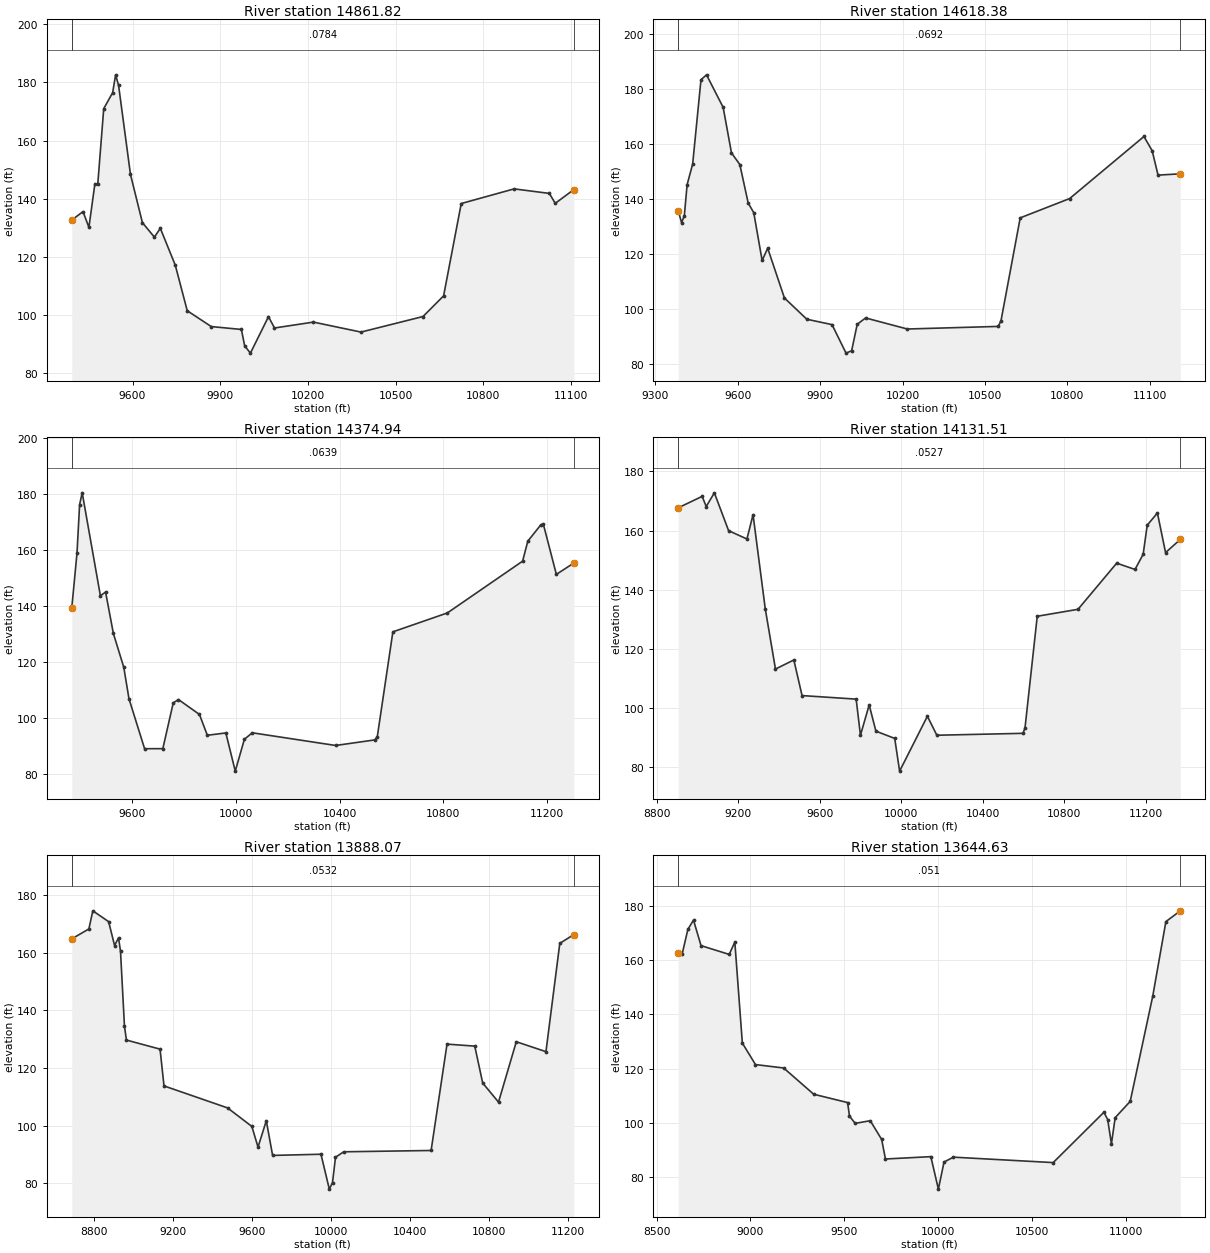
Type RM Length L Ch R = 1 ,14861.82,243.439100,243.439100,243.439100
XS GIS Cut Line= 6
584612.910163732725954.878399369584399.101324916725918.191885407
583835.776535651 725788.22680247 583724.31025151725765.880796695
583442.927473455725724.042020949582921.613078366725672.583716367
#Sta/Elev= 30
9392.098132.69429430.482135.58369450.732130.18949470.982145.00259481.107 145.141
9501.418170.97839531.908176.46399542.071182.59419552.234178.94249592.887148.3554
9633.687131.79829674.584126.82569695.033129.83479746.155 117.1719787.053101.5217
 9869.3296.080199972.22595.093529983.48289.44863 10003.186.9578210064.8899.48806
10085.4595.59717 10218.697.6199710381.2994.1915910593.3999.5385310663.82106.6357
10724.15 138.36310904.97143.400811025.51141.8448 11045.6138.432811109.27143.1611
#Mann= 3 , 0 , 0
9392.098  0.0784       09392.098  0.0784       011109.27  0.0784       0
#XS Ineff= 2 , 0
       0                               0
Bank Sta=9392.098,11109.27
Exp/Cntr=0.3,0.1

Type RM Length L Ch R = 1 ,14618.38,243.439200,243.439200,243.439200
XS GIS Cut Line= 6
584677.109836357725696.769511559584474.744333623725669.365791025
583974.380588894725575.503858393583799.098473625725550.567819247
583633.165680476725537.658825532582862.862509584725499.857044147
#Sta/Elev= 30
9383.215 135.8989395.404131.50979405.469134.07029415.551145.31799435.742152.8357
9466.029183.4446 9486.22185.24049546.794173.40779577.081156.86789607.471152.6511
9637.914138.6547 9658.21135.14719688.654117.7882 9708.95 122.2269769.886104.1535
9851.454 96.42999943.21894.474569994.19884.1188210014.56 84.9774 10034.994.59028
10065.41 96.9038 10217.3 92.882910548.3593.8259310558.3695.8450210628.43 133.271
 10808.6140.293611078.93 162.83211108.99157.6316 11130.2148.797411211.34149.2727
#Mann= 3 , 0 , 0
9383.215  0.0692       09383.215  0.0692       011211.34  0.0692       0
#XS Ineff= 2 , 0
       0                               0
Bank Sta=9383.215,11211.34
Exp/Cntr=0.3,0.1

Type RM Length L Ch R = 1 ,14374.94,243.439100,243.439100,243.439100
XS GIS Cut Line= 6
584745.172385696 725423.13028268584304.068463823725389.123073794
583990.364627379725335.630836764583504.819018946725371.436278342
583325.929022785725377.195516869582817.619556882725366.842763203
#Sta/Elev= 30
 9367.15 139.315 9387.35 158.9699397.364176.24399407.378180.43029477.477143.6911
9497.505144.99679527.547130.21279567.644118.14749587.701106.91489647.87289.08398
9718.20189.101559758.444105.48249778.565106.62529859.386101.31169889.77393.88267
9961.15894.708329997.40981.0797610032.6392.4517110063.1494.7659210384.36 90.2379
10534.9192.2189210544.9493.3258410605.07130.801810815.18137.552211105.22156.0374
11125.23163.167911175.25168.978311185.25169.213911235.29151.319111302.74 155.371
#Mann= 3 , 0 , 0
 9367.15  0.0639       0 9367.15  0.0639       011302.74  0.0639       0
#XS Ineff= 2 , 0
       09833.242                       0
Bank Sta=9367.15,11302.74
Exp/Cntr=0.3,0.1

Type RM Length L Ch R = 1 ,14131.51,243.439100,243.439100,243.439100
XS GIS Cut Line= 6
585192.452727022724941.250419109584751.132121111724949.176657522
584378.995017299725000.577839744583963.065320701725225.696119324
583702.561457033725296.707828995582802.616757047725322.734531688
#Sta/Elev= 30
8904.263167.71219021.716171.58319041.716168.1491 9081.72172.77619151.729159.9886
9241.763157.18549271.788165.3966 9331.84133.58789381.952113.25239472.253116.3204
9512.517 104.2929778.374103.09419799.478 90.89559842.311101.13249875.44392.27127
9967.83389.818659991.87578.7717910128.36   97.3210174.8190.8963910597.7891.54009
10607.8293.3074110668.05131.084810868.34133.429211058.37149.019611148.38146.8904
11188.39 152.015 11208.4161.860211258.42165.964711298.43152.591711370.91157.0448
#Mann= 3 , 0 , 0
8904.263  0.0527       08904.263  0.0527       011370.91  0.0527       0
#XS Ineff= 2 , 0
       0  9833.6                       0
Bank Sta=8904.263,11370.91
Exp/Cntr=0.3,0.1

Type RM Length L Ch R = 1 ,13888.07,243.439200,243.439200,243.439200
XS GIS Cut Line= 6
585221.518679536724769.090546516584714.666441953724774.821967049
584374.572049233724814.418895752583990.349869995724969.371460759
583506.018538011725093.343397417582733.972362418725120.920011476
#Sta/Elev= 30
 8688.67164.8915 8775.19 168.3348795.191174.63268875.192170.87418905.193162.5637
8925.195165.23928935.196160.61568955.198134.55818965.199129.72099135.256126.5661
9155.269113.78889476.911 106.1439599.637 99.71019630.85692.527329672.752101.6754
 9704.6589.633349949.33890.044459991.46677.9196310007.7380.2058110022.7889.00637
10064.5490.8931310506.4691.3483310586.92128.312110727.29127.613610767.34114.8028
 10847.4108.156510937.41129.135811087.42125.694111157.43163.332511228.49166.3745
#Mann= 3 , 0 , 0
 8688.67  0.0532       0 8688.67  0.0532       011228.49  0.0532       0
#XS Ineff= 2 , 0
       09658.126                       0
Bank Sta=8688.67,11228.49
Exp/Cntr=0.3,0.1

Type RM Length L Ch R = 1 ,13644.63,243.439100,243.439100,243.439100
XS GIS Cut Line= 6
585296.391037422724669.937761231584529.530091487724675.411723209
583970.675234781724738.403377564583376.151719527724780.394377885
582970.027410098724793.933246087582628.208289127 724790.38362855
#Sta/Elev= 30
8615.459162.51758636.852162.28338666.855171.26368696.857174.62378736.861165.2415
8886.869162.01288916.869166.53628956.869129.37649026.869121.46729176.887120.2169
9336.967110.55149517.403107.48719527.449102.52469557.65199.830089638.196100.8086
9698.79693.923149718.99686.719129960.76687.5877110000.84 75.6332 10030.985.59809
10080.9987.3962610612.32 85.399410882.47103.928410902.48101.240410922.4992.31133
10942.49101.941811022.49107.925611142.49146.6338 11212.5174.086211289.32178.0515
#Mann= 3 , 0 , 0
8615.459   0.051       08615.459   0.051       011289.32   0.051       0
#XS Ineff= 2 , 0
       0                               0
Bank Sta=8615.459,11289.32
Exp/Cntr=0.3,0.1

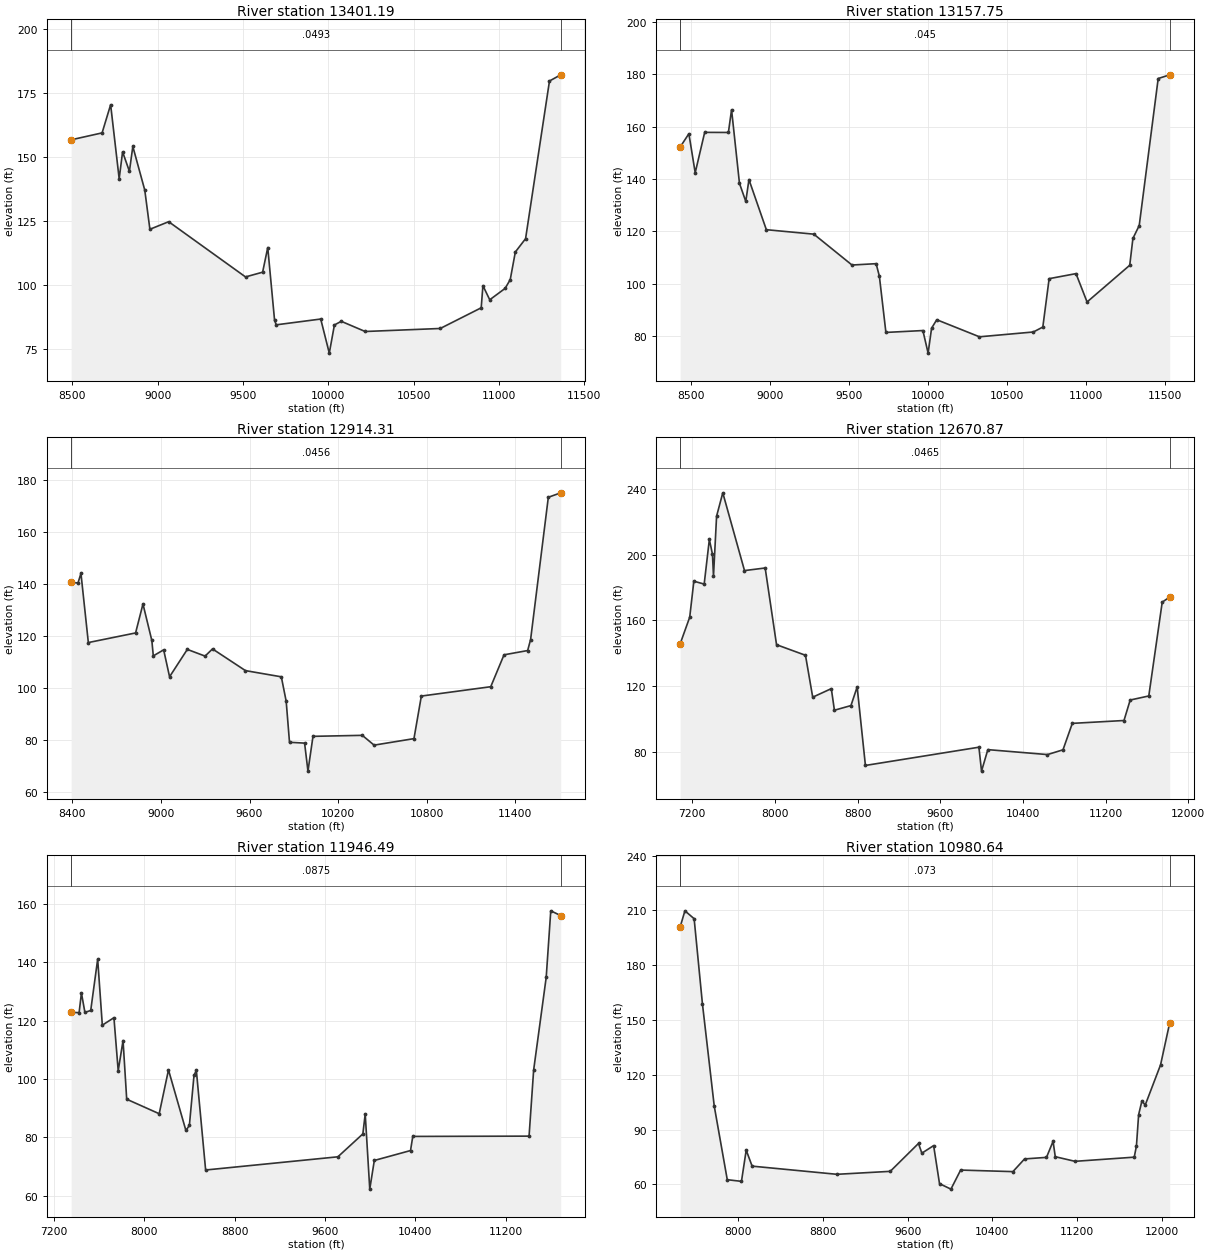
Type RM Length L Ch R = 1 ,13401.19,243.439100,243.439100,243.439100
XS GIS Cut Line= 6
585406.383272809724539.726364924584756.180567401724527.644083574
584467.942696306724517.603853974584041.361867944724493.014757789
583721.363567061724507.398924871582539.217487929724499.854836434
#Sta/Elev= 30
8493.071156.81638674.477159.52438724.487  170.558774.497141.58958794.501152.1051
8834.508144.49368854.512 154.2188924.526137.13958954.532121.82719064.553 124.791
9514.864103.18849615.048 105.0449645.115114.68759685.20386.156319695.225 84.4569
9955.53786.7196510005.6773.3859310035.7684.4003510075.8785.8289310215.9181.84533
10655.9183.0255910895.9191.1115110905.9199.7794710945.9194.2496411035.91 98.7006
11065.92102.116511095.92112.941111155.92 118.15211295.95179.819211361.76182.2339
#Mann= 3 , 0 , 0
8493.071  0.0493       08493.071  0.0493       011361.76  0.0493       0
#XS Ineff= 2 , 0
       0                               0
Bank Sta=8493.071,11361.76
Exp/Cntr=0.3,0.1

Type RM Length L Ch R = 1 ,13157.75,243.439200,243.439200,243.439200
XS GIS Cut Line= 6
585480.257003189724452.272904692584819.712601742724436.090717405
584384.115212665724397.172724113583763.737666502724198.160596571
583592.572969044724165.263796492582422.126263299724137.690461096
#Sta/Elev= 30
8432.775152.19048488.038157.27118528.041142.35668588.054157.79518738.091157.7557
8758.096166.46488808.109138.29668848.119131.38818868.124139.7382 8978.17120.5755
9278.601  118.879520.092 107.0669672.873 107.5829693.348 102.7919734.69381.28939
9968.73582.0108910001.7973.3748210023.7582.9160210056.4786.14517 10326.679.61674
10667.58  81.45910727.5983.3434410767.59101.849410937.59103.778811007.5992.93122
 11277.6 106.97611297.61 117.22211337.61122.173711457.64178.385311530.53179.7978
#Mann= 3 , 0 , 0
8432.775   0.045       08432.775   0.045       011530.53   0.045       0
#XS Ineff= 2 , 0
       0                               0
Bank Sta=8432.775,11530.53
Exp/Cntr=0.3,0.1

Type RM Length L Ch R = 1 ,12914.31,243.439100,243.439100,243.439100
XS GIS Cut Line= 6
585621.430562636724285.148323283584501.399849031724222.970944559
584244.954952433724147.349686285583910.800182698723983.359593318
583767.662035156723956.332131451582361.122826636 723954.68015108
#Sta/Elev= 30
8391.455140.67218437.889140.4742 8457.89144.14818507.893117.5304 8827.96121.2311
 8877.98132.36648938.003118.33218948.007112.40059018.093114.72739058.141104.3585
9178.288114.89389298.702112.31849349.021115.08239572.176106.72749815.153 104.344
9848.09994.924159870.56579.145219972.76978.825669995.59868.0427410029.6581.43237
 10363.681.8174510443.6178.0451710713.6480.5526910763.6596.9359311233.68100.5326
11323.68112.812911483.69114.456311503.69118.677111623.71173.452511707.62175.1627
#Mann= 3 , 0 , 0
8391.455  0.0456       08391.455  0.0456       011707.62  0.0456       0
#XS Ineff= 2 , 0
       0                10911.44       0
Bank Sta=8391.455,11707.62
Exp/Cntr=0.3,0.1

Type RM Length L Ch R = 1 ,12670.87,724.382800,724.382800,724.382800
XS GIS Cut Line= 6
587077.549139554723982.617526793584675.783564607723924.103304144
584334.359369172723887.451790849584087.741493146723811.097403427
583500.378709978723893.515148376582362.526498914723911.738208217
#Sta/Elev= 30
7082.355145.73247174.935161.97177214.949183.85467314.982182.10737364.999209.2392
7395.009 200.3137405.012186.85617435.022223.42967495.042237.61947705.113190.3152
7905.179191.89788015.201145.22938295.253138.79648365.267113.3037  8545.3118.5002
8575.306105.36978735.336108.19198795.347119.52458875.36271.778289973.78182.87289
    999968.32163 10060.281.3944310637.3178.3904410787.5581.2887510877.6397.37514
11377.7899.1171711437.79111.572211617.79114.0466 11747.8171.112711820.28174.2137
#Mann= 3 , 0 , 0
7082.355  0.0465       07082.355  0.0465       011820.28  0.0465       0
#XS Ineff= 2 , 0
       09828.165        10972.99       0
Bank Sta=7082.355,11820.28
Exp/Cntr=0.3,0.1

Type RM Length L Ch R = 1 ,11946.49,965.843800,965.843800,965.843800
XS GIS Cut Line= 6
586503.601734549 723772.11706683584340.088242173723253.880114019
584049.383064858723306.515023868583685.921551551723279.445563701
583385.180277884723289.399298832582247.976011187723464.353801399
#Sta/Elev= 30
 7351.55122.85327422.092122.80297442.658129.52157473.507122.88637524.921 123.528
7586.618141.1339 7627.75118.49837730.579121.05627768.459102.86117811.388113.2261
 7843.69 93.10138131.61188.125148213.874103.14458368.11782.384028398.96684.10853
8440.098101.31598460.663102.99678542.92668.823939714.61773.35171 9935.7881.19951
9956.69588.018849996.96962.2661510037.3572.0966110358.0675.4959410378.0780.33992
11408.2880.4421811448.75103.079511560.04134.873511600.51157.710711688.56156.0797
#Mann= 3 , 0 , 0
 7351.55  0.0875       0 7351.55  0.0875       011688.56  0.0875       0
#XS Ineff= 2 , 0
       0 9808.59        10520.44       0
Bank Sta=7351.55,11688.56
Exp/Cntr=0.3,0.1

Type RM Length L Ch R = 1 ,10980.64,482.921900,482.921900,482.921900
XS GIS Cut Line= 6
586443.224613845 723455.13718307585155.179371864722811.114562094
584334.885748166722615.462851543 583897.11427716722376.637379192
583443.921556906722351.461911571582121.619981557722711.077470914
#Sta/Elev= 30
7450.234200.91147495.262209.73057582.413205.40617660.676 158.8587772.479102.7773
7895.46362.527768029.62761.623438074.34878.69345 8130.2569.954448931.623 65.4845
9435.41267.106939702.25282.386439733.899 77.04719845.21481.193379900.79960.36185
 10008.657.3686910100.3767.8037610594.3666.9509410704.3673.9033210911.5974.75032
10973.7783.5394110994.4975.1167711181.0372.5894411740.6474.8672211761.3781.01269
 11782.198.1293411813.19105.672611844.28 103.38511989.36125.417112075.77 148.431
#Mann= 3 , 0 , 0
7450.234   0.073       07450.234   0.073       012075.77   0.073       0
#XS Ineff= 2 , 0
       09753.772        10702.66       0
Bank Sta=7450.234,12075.77
Exp/Cntr=0.3,0.1

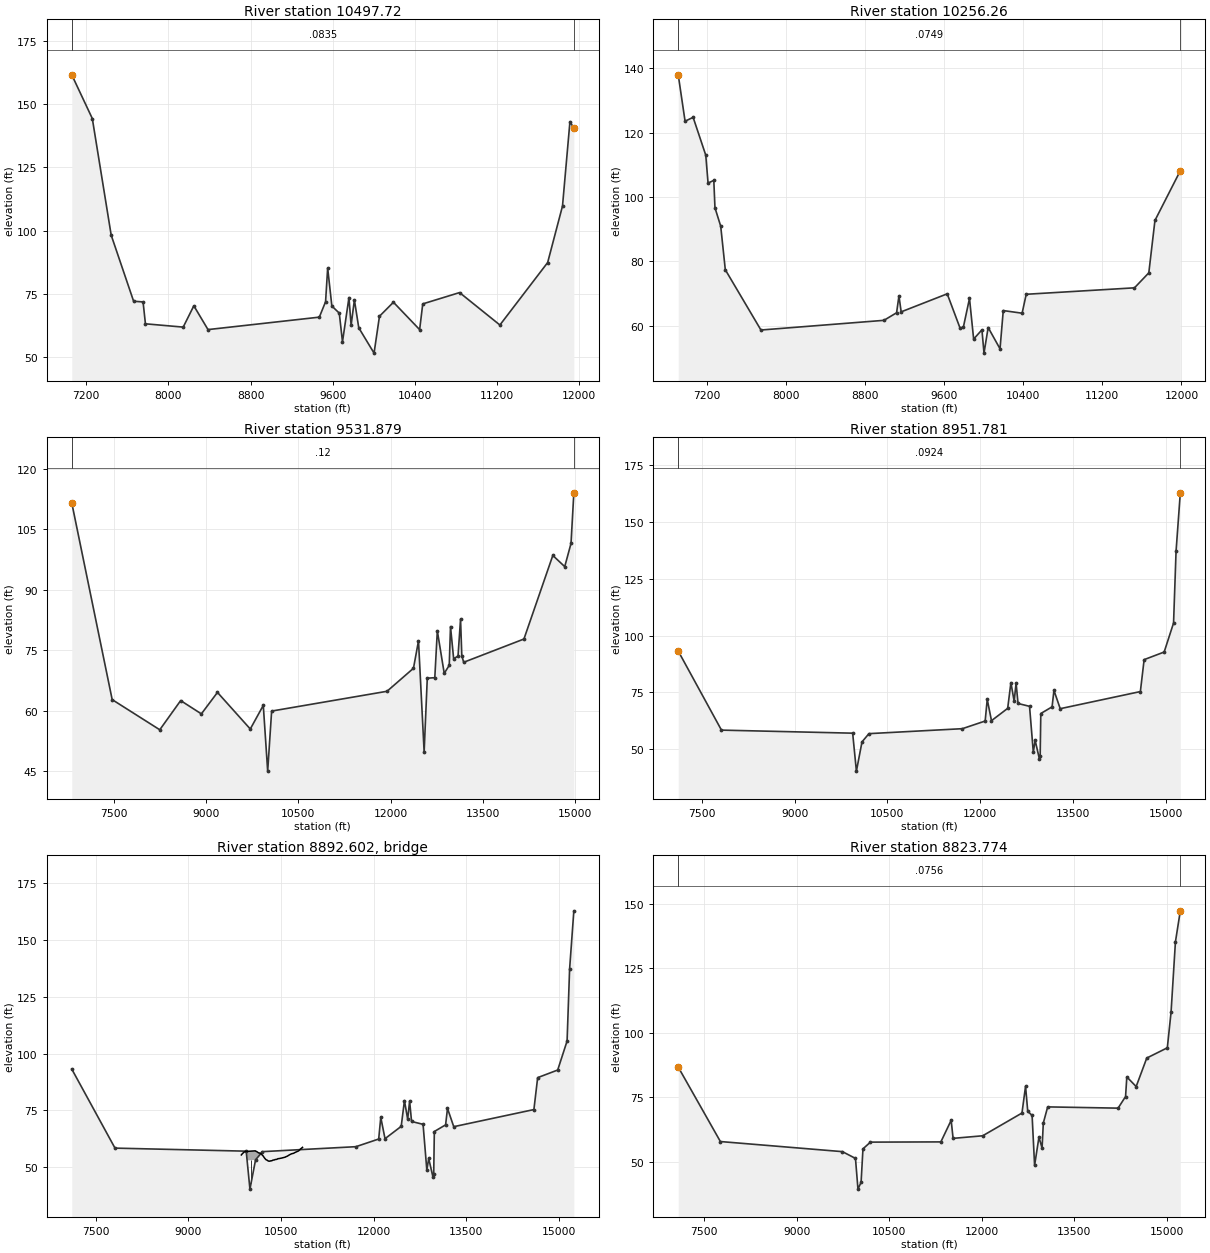
Type RM Length L Ch R = 1 ,10497.72,241.461000,241.461000,241.461000
XS GIS Cut Line= 6
 586569.01028201723077.780178592584521.352342993721916.407699883
584233.398699671721976.108363882583741.721611053722140.992593557
583380.407780826722198.359595209582068.161661327722540.982815638
#Sta/Elev= 30
 7058.71161.5908 7258.76144.31097442.70398.192357661.13672.071727753.10871.81278
  7776.1 63.15498143.987 61.84968247.45570.276178385.41260.870199469.71165.78847
9530.53871.878279550.91585.202729591.75670.181699663.96967.377439695.18856.03541
9758.19173.525529779.26862.59004  9811.272.575069853.77661.58046 10002.751.56446
10055.4366.1435710191.4571.6808210446.6260.8508610476.9171.02587 10835.575.50316
11228.2462.6818311693.3387.3742111838.02109.720711910.37143.070211948.44140.5182
#Mann= 3 , 0 , 0
 7058.71  0.0835       0 7058.71  0.0835       011948.44  0.0835       0
#XS Ineff= 2 , 0
       09811.827         10533.1       0
Bank Sta=7058.71,11948.44
Exp/Cntr=0.3,0.1

Type RM Length L Ch R = 1 ,10256.26,724.382800,724.382800,724.382800
XS GIS Cut Line= 6
586644.481682867722901.680243149584676.315134406721736.543856055
584357.246852666721742.193654925584105.349006057721777.511735097
583533.896265209721977.961369216581977.176096022722380.978780583
#Sta/Elev= 30
6912.695138.01826981.818123.5927 7063.22124.79977190.994113.03667214.236104.3617
 7272.34105.19097283.961 96.68867342.06690.954717388.54977.411057748.79758.66772
8992.23361.677479120.06364.029449144.02169.260639166.54764.316699631.91369.92128
9761.17159.313799794.75359.488769857.17768.493629899.10155.858999982.94958.72138
10003.8951.4818710045.8859.4450310165.8852.82834 10198.664.7141510389.2963.89426
10430.5169.7810911525.1471.78692   1167076.4440411732.0892.73616 11988.5 108.193
#Mann= 3 , 0 , 0
6912.695  0.0749       06912.695  0.0749       0 11988.5  0.0749       0
#XS Ineff= 2 , 0
       09846.542        10479.77       0
Bank Sta=6912.695,11988.5
Exp/Cntr=0.3,0.1

Type RM Length L Ch R = 1 ,9531.879,580.097600,580.097600,580.097600
XS GIS Cut Line= 6
586674.670243233722755.768868089584949.325428993721574.987941027
 584447.91558072721513.597655877583440.172418326721271.656315401
581634.288886338          721845 579059.91618669722356.308618486
#Sta/Elev= 30
6819.813111.56047476.30262.738198249.29355.254468588.58662.499748924.908    59.2
9186.20864.530379719.47955.442859930.76861.3116710002.0444.9898510066.1559.89495
11940.49 64.808612370.0870.5188912451.6577.31121 12543.449.7698212594.3868.04937
12716.7268.1877712757.5179.8153512869.6569.2554312951.2271.2481312971.6180.87252
13022.5872.8939113093.95 73.543313134.7382.7205613155.1273.6579613185.7172.00498
14164.46 77.780414633.4598.5233114827.1695.7506814929.11101.512314975.08114.0676
#Mann= 3 , 0 , 0
6819.813    0.12       06819.813    0.12       014975.08    0.12       0
#XS Ineff= 2 , 0
       09766.443        10376.15       0
Bank Sta=6819.813,14975.08
Exp/Cntr=0.3,0.1

Type RM Length L Ch R = 1 ,8951.781,128.006900,128.006900,128.006900
XS GIS Cut Line= 6
586589.135988891722534.386092141585191.221773177721352.422231317
584466.061562806720910.431542784583394.899972469721068.449085698
581635.635252237721617.611829877579157.113132507722020.979155242
#Sta/Elev= 30
7115.58493.180297815.05858.369579937.846 57.02759998.31340.3113910089.0153.19184
10201.1956.8186911712.46 59.001912081.6262.3749612115.1871.9061412183.94 62.5286
12445.8467.9505412498.2279.29061 12550.671.1034412582.0379.0865912613.45 70.1018
12799.5968.8479912860.3848.7299712890.7753.8112212960.7845.4951912971.8247.08892
12981.9665.6882313164.3268.6169413194.7275.8624613296.0367.8116114592.8775.34757
14653.6689.4113114977.8792.7602215129.85105.539715170.37137.160915239.15162.8717
#Mann= 3 , 0 , 0
7115.584  0.0924       07115.584  0.0924       015239.15  0.0924       0
#XS Ineff= 2 , 0
       09757.875        10703.33       0
Bank Sta=7115.584,15239.15
Exp/Cntr=0.3,0.1

Type RM Length L Ch R = 3 ,8892.602,,,
BEGIN DESCRIPTION:
END DESCRIPTION:
Bridge Culvert--1,0,-1,-1, 0
Deck Dist Width WeirC Skew NumUp NumDn MinLoCord MaxHiCord MaxSubmerge Is_Ogee
28.003450,72.000000,2.6,0, 45, 45, , , 0.95, 0, 0,0,,
 9859.21 9873.42 9893.67 9913.92 9924.04 9956.07 9956.0710081.0710081.0710086.04
10096.1610106.2910136.6610146.3910156.9110187.2810197.4110207.5310237.9110258.21
10278.7710289.0610299.3410319.9010330.1810340.4610361.0310371.3110391.8710402.15
10433.0010453.7210464.1610509.8710568.6210579.0610599.9510641.7210672.5310703.34
10733.7710783.8310803.8610813.8710849.48
   55.36   55.84   56.39   56.80   56.94   56.94   56.94   57.17   57.17   57.17
   56.95   56.88   56.30   56.21   56.23   55.65   55.29   55.06   53.89   53.27
   53.03   52.79   52.66   52.62   52.75   52.75   52.91   53.11   53.15   53.32
   53.43   53.75   53.73   53.98   54.39   54.57   54.78   55.48   55.88   56.08
   56.53   57.12   57.60   57.93   58.72
 -944.64 -944.16 -943.61 -943.20 -943.06 -943.06   52.94   53.17 -942.83 -942.83
 -943.05 -943.12 -943.70 -943.79 -943.77 -944.35 -944.71 -944.94 -946.11 -946.73
 -946.97 -947.21 -947.34 -947.38 -947.25 -947.25 -947.09 -946.89 -946.85 -946.68
 -946.57 -946.25 -946.27 -946.02 -945.61 -945.43 -945.22 -944.52 -944.12 -943.92
 -943.47 -942.88 -942.40 -942.07 -941.28
 9859.21 9873.42 9893.67 9913.92 9924.04 9952.18 9952.1810077.1810077.1810086.04
10096.1610106.2910136.6610146.3910156.9110187.2810197.4110207.5310237.9110258.21
10278.7710289.0610299.3410319.9010330.1810340.4610361.0310371.3110391.8710402.15
10433.0010453.7210464.1610509.8710568.6210579.0610599.9510641.7210672.5310703.34
10733.7710783.8310803.8610813.8710849.48
   55.36   55.84   56.39   56.80   56.94   56.94   56.94   57.16   57.16   57.17
   56.95   56.88   56.30   56.21   56.23   55.65   55.29   55.06   53.89   53.27
   53.03   52.79   52.66   52.62   52.75   52.75   52.91   53.11   53.15   53.32
   53.43   53.75   53.73   53.98   54.39   54.57   54.78   55.48   55.88   56.08
   56.53   57.12   57.60   57.93   58.72
 -944.64 -944.16 -943.61 -943.20 -943.06 -943.06   52.94   53.16 -942.84 -942.83
 -943.05 -943.12 -943.70 -943.79 -943.77 -944.35 -944.71 -944.94 -946.11 -946.73
 -946.97 -947.21 -947.34 -947.38 -947.25 -947.25 -947.09 -946.89 -946.85 -946.68
 -946.57 -946.25 -946.27 -946.02 -945.61 -945.43 -945.22 -944.52 -944.12 -943.92
 -943.47 -942.88 -942.40 -942.07 -941.28
Pier Skew, UpSta & Num, DnSta & Num=  ,10018.57, 2 ,10014.68, 2 , 0 , 0 , 0 ,,
    4.00    4.00
 -942.94   57.06
    4.00    4.00
 -942.95   57.05
BR Coef=-1 , 0 , 0 ,, 0 ,,,0.8,0,1,0,
WSPro=,,,, 1 ,,,, 0 ,,,, 0 ,,,,-1 ,-1 ,-1 , 0 , 0 , 0 , 0 , 0
BC Design=,, 0 ,, 0 ,,,,,,

Type RM Length L Ch R = 1 ,8823.774,558.231800,558.231800,558.231800
XS GIS Cut Line= 6
586629.387402713 722423.69470416585226.698346645721250.480928555
584498.021091372720790.263714716583390.040125191720985.831681713
581640.495099515721510.695189416579176.552521706721870.323889136
#Sta/Elev= 30
7077.10486.615227760.73557.75665    974053.83972 9951.4351.221079991.92839.31018
10042.5541.9556110072.9254.9306610194.4257.5317611336.2657.6192811503.3165.98845
11534.6358.9910112014.8859.9910612651.7468.8108912709.7179.2003112745.1969.48995
12815.9367.8677612856.3548.49954 12927.159.4766212977.6355.2080512997.84 64.9416
13068.5871.1912714210.5570.7058114331.8275.2095914352.0482.8038214503.6279.07573
14675.43 90.124515008.9294.0960815069.56107.8822 15140.3135.152415219.58147.1988
#Mann= 3 , 0 , 0
7077.104  0.0756       07077.104  0.0756       015219.58  0.0756       0
#XS Ineff= 2 , 0
       09678.455        10673.35       0
Bank Sta=7077.104,15219.58
Exp/Cntr=0.3,0.1

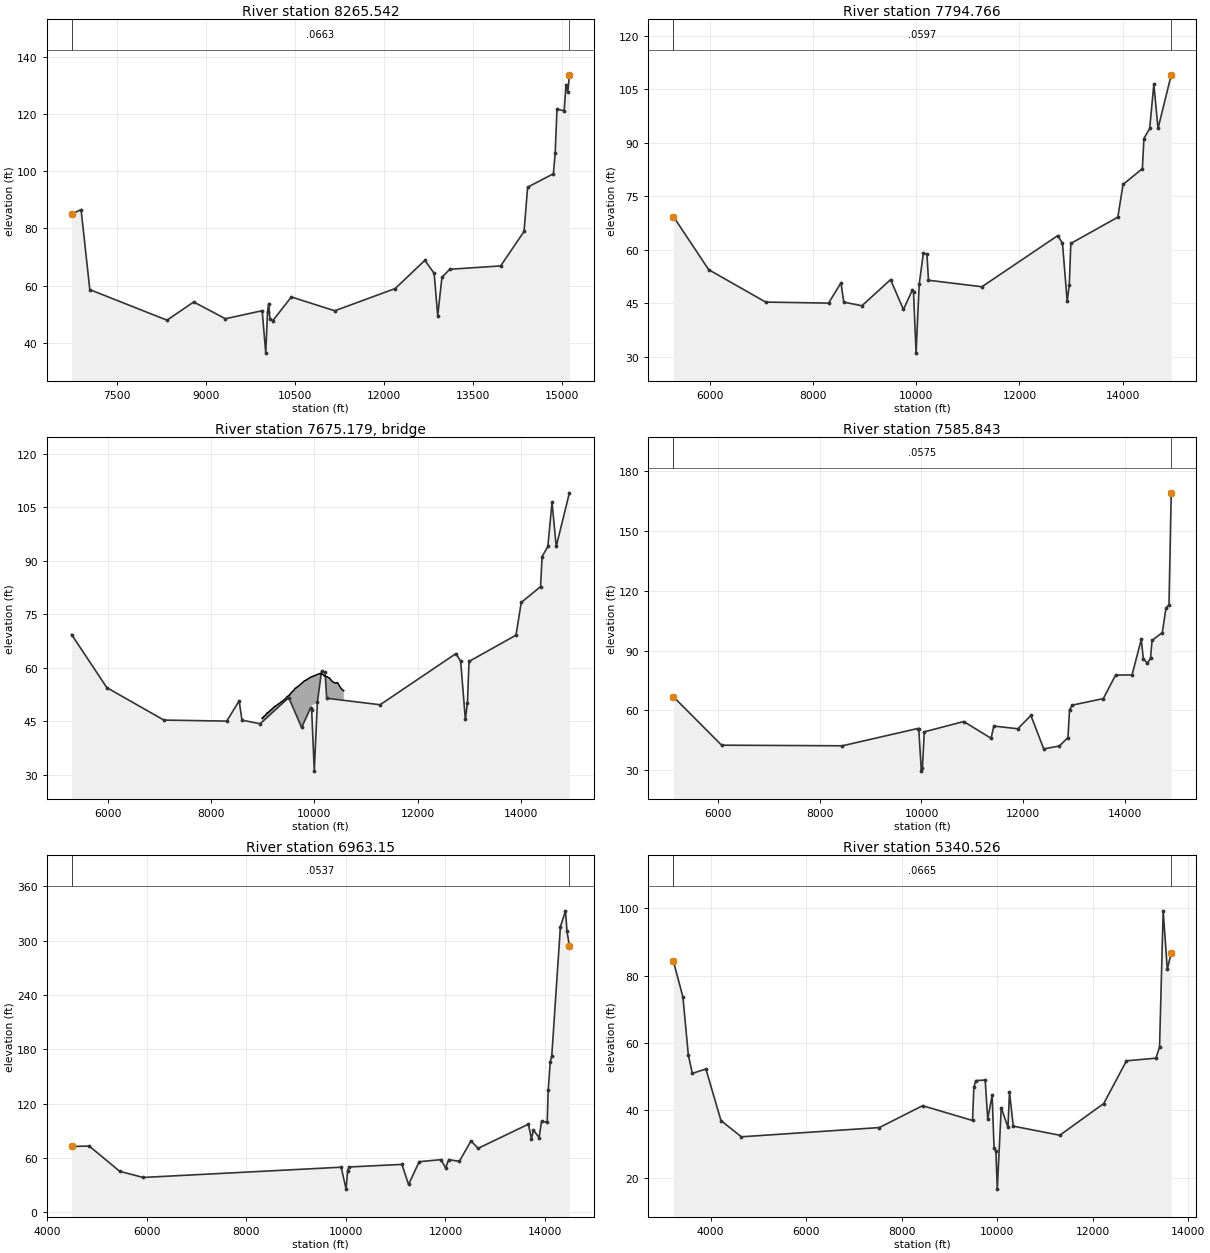
Type RM Length L Ch R = 1 ,8265.542,470.776500,470.776500,470.776500
XS GIS Cut Line= 5
586941.335859865722051.369126394584585.693078458720284.361251712
584011.323355079720242.511903718581616.195863038721102.468016773
579307.768398613721447.517174616
#Sta/Elev= 30
6728.24984.911456888.84886.568747036.18658.596148338.70347.923618788.65854.28467
9323.81548.424889944.37951.2342210004.5436.4137510034.6250.8638110054.6753.74939
10074.7248.2860110124.8647.80408 10436.256.0294111169.3351.2100112189.3358.98146
12688.7168.8324512845.4564.3104112906.1249.48715 12976.962.8963813108.3465.70287
13967.7966.8818814362.1278.9066814422.79 94.369614857.5699.08249 14887.9106.2798
14918.23121.654315039.56121.0663 15069.9130.161315100.23127.582215127.76133.6288
#Mann= 3 , 0 , 0
6728.249  0.0663       06728.249  0.0663       015127.76  0.0663       0
#XS Ineff= 2 , 0
       09442.185        10435.41       0
Bank Sta=6728.249,15127.76
Exp/Cntr=0.3,0.1

Type RM Length L Ch R = 1 ,7794.766,208.922700,208.922700,208.922700
XS GIS Cut Line= 6
588143.846847355721865.206337512585196.793980122719564.617448553
 584380.77339977 719786.53310962583526.115849406719853.487262338
581659.934488684720611.623440117579502.162290365720932.373361498
#Sta/Elev= 30
5298.48269.347035982.07454.45532 7086.4345.372688303.65145.088318544.68950.77676
8597.77645.361498950.64844.34549 9504.3951.66809 9753.5643.298389928.68548.82697
9948.69648.168579998.72331.0731110058.7650.30877 10138.859.0746410208.8458.79144
10238.8551.4890211273.7449.6695112741.6963.9958812833.7161.8486712924.6945.54385
12965.1350.2544712995.4661.8050413905.3569.1639414006.4578.3275814380.5282.75678
14410.8591.2012414522.0694.0044214602.93106.440214683.81 94.006714939.43109.0406
#Mann= 3 , 0 , 0
5298.482  0.0597       05298.482  0.0597       014939.43  0.0597       0
#XS Ineff= 2 , 0
       09632.687        10212.83       0
Bank Sta=5298.482,14939.43
Exp/Cntr=0.3,0.1

Type RM Length L Ch R = 3 ,7675.179,,,
BEGIN DESCRIPTION:
END DESCRIPTION:
Bridge Culvert--1,0,-1,-1, 0
Deck Dist Width WeirC Skew NumUp NumDn MinLoCord MaxHiCord MaxSubmerge Is_Ogee
68.461350,72.000000,2.6,0, 60, 60, , , 0.95, 0, 0,0,,
 8987.23 8992.80 9003.54 9025.03 9035.77 9068.01 9078.75 9088.56 9100.24 9121.73
 9132.47 9143.26 9153.65 9164.07 9178.77 9205.73 9247.40 9257.82 9309.90 9321.63
 9330.73 9341.15 9392.41 9413.29 9433.01 9473.62 9514.22 9529.69 9544.68 9554.83
 9605.58 9625.88 9636.03 9646.19 9676.67 9686.84 9809.74 9859.82 9890.35 9900.52
 9931.10 9949.10 9949.1010084.1010084.1010114.5510124.7410145.1310165.5210175.71
10206.3010247.0710277.6510293.6110338.0610398.2010448.4710508.0510531.9610568.85
   45.87   45.98   46.00   46.46   46.52   46.93   47.27   47.23   47.50   47.65
   47.93   47.95   48.10   48.37   48.41   48.85   49.34   49.38   49.95   49.97
   50.08   50.32   50.75   51.07   51.24   51.95   52.31   52.65   52.82   53.08
   53.76   54.22   54.36   54.34   54.75   54.81   56.38   56.71   57.08   57.11
   57.44   57.49   57.49   58.30   58.30   58.44   58.35   58.33   58.16   57.98
   57.66   57.51   57.21   57.17   56.31   55.73   55.86   54.44   54.03   53.59
 -954.13 -954.02 -954.00 -953.54 -953.48 -953.07 -952.73 -952.77 -952.50 -952.35
 -952.07 -952.05 -951.90 -951.63 -951.59 -951.15 -950.66 -950.62 -950.05 -950.03
 -949.92 -949.68 -949.25 -948.93 -948.76 -948.05 -947.69 -947.35 -947.18 -946.92
 -946.24 -945.78 -945.64 -945.66 -945.25 -945.19 -943.62 -943.29 -942.92 -942.89
 -942.56 -942.51   49.49   50.30 -941.70 -941.56 -941.65 -941.67 -941.84 -942.02
 -942.34 -942.49 -942.79 -942.83 -943.69 -944.27 -944.14 -945.56 -945.97 -946.41
 8987.23 8992.80 9003.54 9025.03 9035.77 9068.01 9078.75 9088.56 9100.24 9121.73
 9132.47 9143.26 9153.65 9164.07 9178.77 9205.73 9247.40 9257.82 9309.90 9321.63
 9330.73 9341.15 9392.41 9413.29 9433.01 9473.62 9514.22 9529.69 9544.68 9554.83
 9605.58 9625.88 9636.03 9646.19 9676.67 9686.84 9809.74 9859.82 9890.35 9900.52
 9931.10 9951.55 9951.5510086.5510086.5510114.5510124.7410145.1310165.5210175.71
10206.3010247.0710277.6510293.6110338.0610398.2010448.4710508.0510531.9610568.85
   45.87   45.98   46.00   46.46   46.52   46.93   47.27   47.23   47.50   47.65
   47.93   47.95   48.10   48.37   48.41   48.85   49.34   49.38   49.95   49.97
   50.08   50.32   50.75   51.07   51.24   51.95   52.31   52.65   52.82   53.08
   53.76   54.22   54.36   54.34   54.75   54.81   56.38   56.71   57.08   57.11
   57.44   57.51   57.51   58.32   58.32   58.44   58.35   58.33   58.16   57.98
   57.66   57.51   57.21   57.17   56.31   55.73   55.86   54.44   54.03   53.59
 -954.13 -954.02 -954.00 -953.54 -953.48 -953.07 -952.73 -952.77 -952.50 -952.35
 -952.07 -952.05 -951.90 -951.63 -951.59 -951.15 -950.66 -950.62 -950.05 -950.03
 -949.92 -949.68 -949.25 -948.93 -948.76 -948.05 -947.69 -947.35 -947.18 -946.92
 -946.24 -945.78 -945.64 -945.66 -945.25 -945.19 -943.62 -943.29 -942.92 -942.89
 -942.56 -942.49   49.51   50.32 -941.68 -941.56 -941.65 -941.67 -941.84 -942.02
 -942.34 -942.49 -942.79 -942.83 -943.69 -944.27 -944.14 -945.56 -945.97 -946.41
BR Coef=-1 , 0 , 0 ,, 0 ,,,0.8,0,1,0,
WSPro=,,,, 1 ,,,, 0 ,,,, 0 ,,,,-1 ,-1 ,-1 , 0 , 0 , 0 , 0 , 0
BC Design=,, 0 ,, 0 ,,,,,,

Type RM Length L Ch R = 1 ,7585.843,622.692900,622.692900,622.692900
XS GIS Cut Line= 6
588319.946782857721704.200682282585216.015021622719356.680726781
584116.920920789719615.291103452583659.110659391719606.554266408
581339.184567302720470.687868595579521.601679534720728.259775177
#Sta/Elev= 30
5118.87466.818936067.79142.504728443.39242.199289925.66350.877319946.26350.52345
9997.76229.4804110018.3631.2470310055.2549.2099510831.7254.3777411369.46  45.965
11423.2452.0993911896.4650.7491212152.3157.4177312405.9140.6136512712.3642.10988
12881.4346.3174312913.1360.2641612965.9662.60115 13576.9 65.8919 13819.377.71395
14142.4977.7580614324.2995.5873514364.6985.9158214445.4983.6221214506.0986.21129
14536.3995.1109514738.3999.0524514809.09111.178614869.69113.058214913.52169.1806
#Mann= 3 , 0 , 0
5118.874  0.0575       05118.874  0.0575       014913.52  0.0575       0
#XS Ineff= 2 , 0
       09703.551         10173.2       0
Bank Sta=5118.874,14913.52
Exp/Cntr=0.3,0.1

Type RM Length L Ch R = 1 , 6963.15,1622.624600,1622.624600,1622.624600
XS GIS Cut Line= 6
588803.317624152 721754.93898268588089.832536727721190.650832176
585114.927958071718952.010262951584127.854079008718959.506283745
584007.240731448718944.695818454579837.491753638719790.309247509
#Sta/Elev= 30
4493.36972.711014848.21173.174025459.13845.340815927.99338.513559906.48149.81909
10006.4825.6305510036.4846.1843310066.4850.0735511127.2352.93914 11259.830.79954
11473.9555.9096411912.4458.1385812004.2248.96734 12065.458.1586312279.5556.30306
12514.0978.9042612656.8670.6430913666.4197.2933213727.5981.3350813768.3890.86486
13880.5682.4435213931.54 100.71514043.71 99.189614064.11134.9179 14104.9166.0009
14135.49172.572214308.85315.080114410.82332.749314441.42310.300914489.86293.9605
#Mann= 3 , 0 , 0
4493.369  0.0537       04493.369  0.0537       014489.86  0.0537       0
#XS Ineff= 2 , 0
       09801.264        10155.99       0
Bank Sta=4493.369,14489.86
Exp/Cntr=0.3,0.1

Type RM Length L Ch R = 1 ,5340.526,1675.017500,1675.017500,1675.017500
XS GIS Cut Line= 6
589767.205613729721398.171016756 585417.14614014718259.922003164
584833.176935394717794.522756421584152.029209513717198.537627522
583588.116302497 716725.03562638581119.202141461715701.556433413
#Sta/Elev= 30
3219.30684.345843419.31673.629323532.38356.442023616.60750.987923900.21352.28566
4216.06636.969794643.36832.157827531.92934.900178437.80941.393579483.76537.00199
9511.32346.894049550.70648.827769748.87549.02042 9801.7237.431339894.19844.47747
9934.31328.935119972.66527.8555810002.0216.6228810084.5540.8036510225.4435.00068
10257.6745.4159810336.7435.3193211310.5832.6205412230.7242.0328912707.0354.72061
13324.0655.5047413399.8458.8391713475.6199.2463313562.2281.9019813644.2786.86629
#Mann= 3 , 0 , 0
3219.306  0.0665       03219.306  0.0665       013644.27  0.0665       0
#XS Ineff= 2 , 0
       09783.893        10176.16       0
Bank Sta=3219.306,13644.27
Exp/Cntr=0.3,0.1

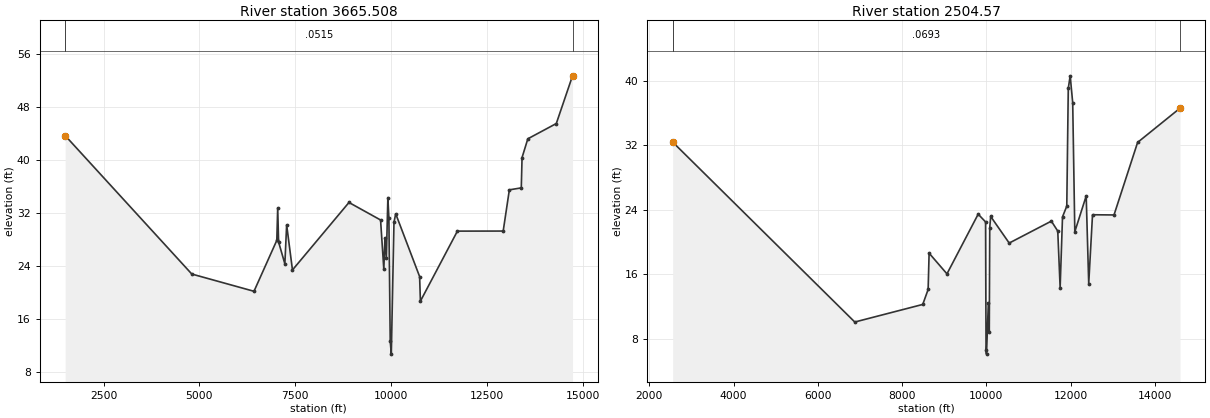
Type RM Length L Ch R = 1 ,3665.508,1160.938100,1160.938100,1160.938100
XS GIS Cut Line= 6
592535.723001003720717.051658064586485.851669967717077.362108767
586054.423754692716729.893944368584879.112924218715654.123427317
583007.776266038715062.979890719580953.378117889714883.399633005
#Sta/Elev= 30
1498.13943.672534801.655 22.78176423.81520.179417018.99627.866867042.33732.76115
7065.67727.61387 7229.0624.321177275.74130.203747427.45423.397198901.31333.58255
9725.684 30.93969810.40323.501399839.00128.19216 9876.36 25.23579916.06434.31764
9942.40631.251419977.51612.6685110005.5810.6970910075.3630.5992110120.7431.87572
 10743.922.4069510764.8718.6927611729.6929.2594112924.3529.2698713084.9635.48822
13396.14 35.785613416.2240.3605813566.7943.1916814309.6145.4953714732.8452.69444
#Mann= 3 , 0 , 0
1498.139  0.0515       01498.139  0.0515       014732.84  0.0515       0
#XS Ineff= 2 , 0
       09403.403        10987.98       0
Bank Sta=1498.139,14732.84
Exp/Cntr=0.3,0.1

Type RM Length L Ch R = 1 , 2504.57,0.000000,0.000000,0.000000
XS GIS Cut Line= 6
592709.334112138718622.867630288587317.714799106715451.651126087
586440.999167681715477.655403271 585326.59692511714969.983270556
584426.820299625714404.527317837581808.180144578714387.758121759
#Sta/Elev= 30
2556.24732.388926877.03610.067468489.646 12.25068617.26214.106358640.46518.60825
9064.16416.042819804.74723.449349980.30722.483429991.2796.56836810002.256.085551
10046.1412.4324310068.098.77149210079.06 21.7371   1010123.16706 10540.7 19.8627
11540.8922.5840811692.9521.3504411749.3314.3414511805.7123.1143111907.0324.44775
11942.4639.0538111987.5640.6081612047.5637.2703312097.5621.2700812367.5725.70828
12427.5714.8377612517.57 23.375413027.5823.3488413587.5932.3478114594.4336.59801
#Mann= 3 , 0 , 0
2556.247  0.0693       02556.247  0.0693       014594.43  0.0693       0
#XS Ineff= 2 , 0
       08928.016        11769.51       0
Bank Sta=2556.247,14594.43
Exp/Cntr=0.3,0.1